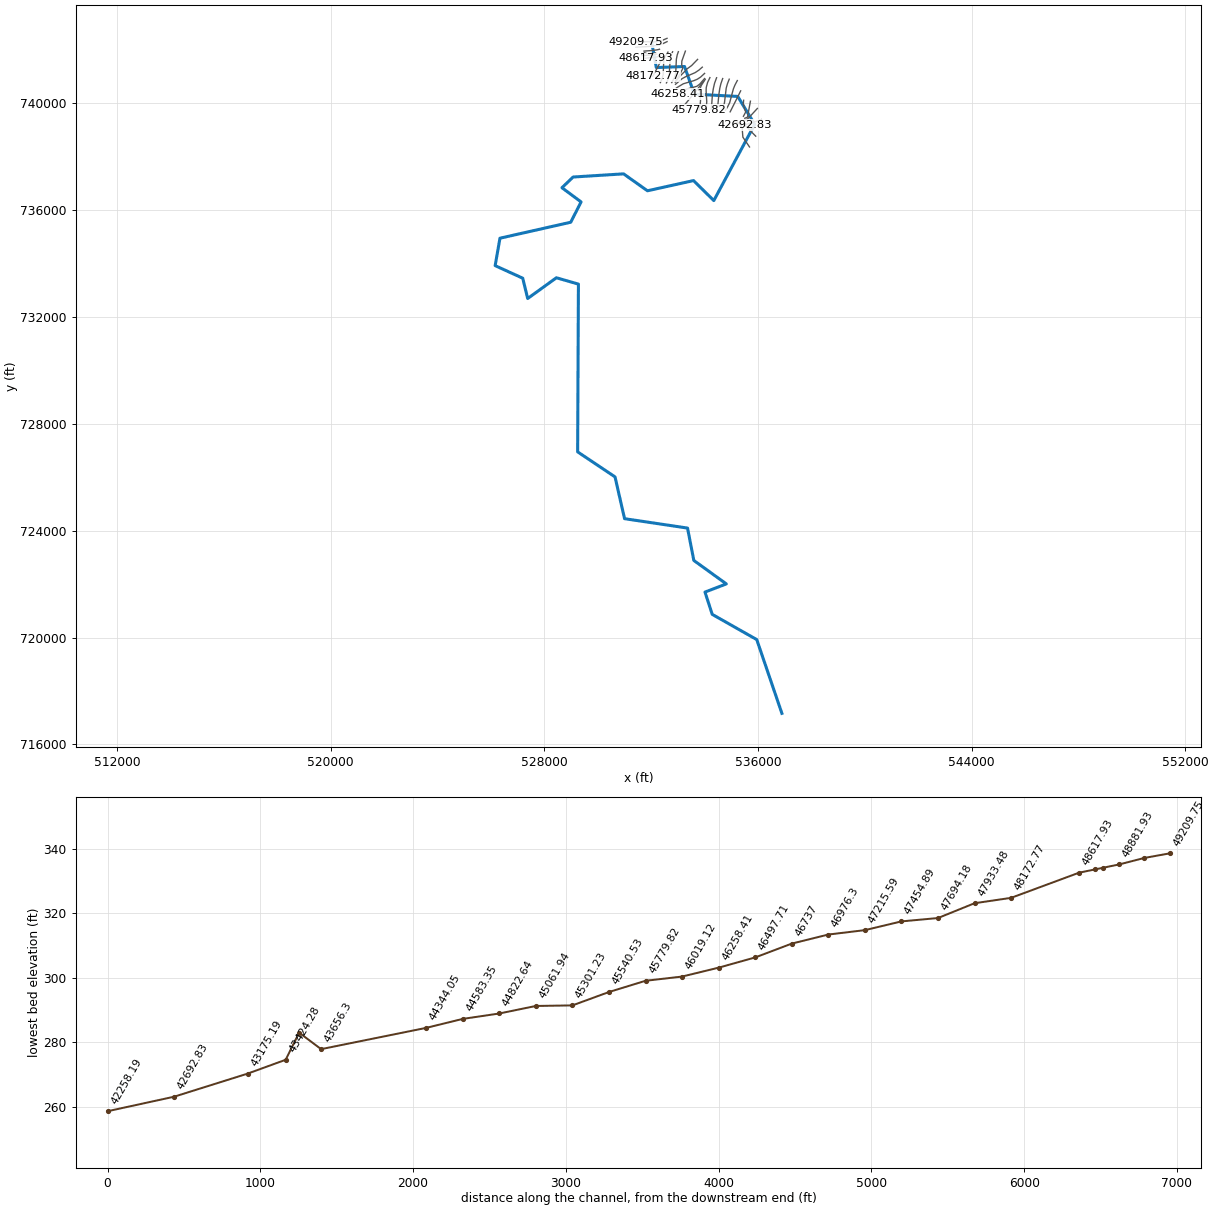
--- 1552_ras.prj (project) ---

Proj Title=1552
Current Plan=p01
Default Exp/Contr=0.3,0.1
English Units
Geom File=g01
Flow File=f01
Plan File=p01
Y Axis Title=Elevation
X Axis Title(PF)=Main Channel Distance
X Axis Title(XS)=Station
BEGIN DESCRIPTION:
RFD model 1552 exported to HEC-RAS
END DESCRIPTION:

--- 1552_ras.p01 (plan) ---

Plan Title=Plan 01
Program Version=4.10
Short Identifier=Plan 01
Geom File=g01
Flow File=f01
Subcritical Flow
Calc Critical at every XS
Secant Critical Depth

--- 1552_ras.f01 (steady flow) ---

Flow Title=Flow 01
Program Version=5.01
Number of Profiles= 6
Profile Names=10yr,25yr,50yr,100yr,100plus,500yr
River Rch & RM=1552,95,49209.75
 6791.7811336.9415784.7519967.4929152.5331074.57
River Rch & RM=1552,95,49045.84
  6792.511338.26 15786.719970.0929156.33 31078.5
River Rch & RM=1552,95,48881.93
 6795.1211343.0915793.8619979.6329170.2731092.91
River Rch & RM=1552,95,48773.04
 6795.4811343.7515794.8419980.9329172.1631094.88
River Rch & RM=1552,95,48617.93
 6813.6411377.7415845.5420048.9129271.4131198.98
River Rch & RM=1552,95,48172.77
 6822.7111394.8415871.1320083.3229321.6431251.96
River Rch & RM=1552,95,47933.48
 6825.6511400.3515879.3720094.3829337.7931268.96
River Rch & RM=1552,95,47694.18
 6829.1211406.8915889.1620107.5429357.0131289.22
River Rch & RM=1552,95,47454.89
 6831.77 11411.915896.6920117.6829371.82 31304.9
River Rch & RM=1552,95,47215.59
 6840.6311428.2915920.9820150.0729419.1131353.89
River Rch & RM=1552,95, 46976.3
 6883.6111506.0816034.8820300.48 29638.731576.26
River Rch & RM=1552,95,   46737
  6889.111516.3316050.1720320.9629668.6131607.52
River Rch & RM=1552,95,46497.71
  6892.311522.3916059.2520333.1929686.4631626.39
River Rch & RM=1552,95,46258.41
 6893.6311524.8916063.0120338.2629693.86 31634.2
River Rch & RM=1552,95,46019.12
 6902.3311541.4316087.8920371.8429742.8831686.24
River Rch & RM=1552,95,45779.82
 6903.63 11543.916091.6120376.8629750.2131694.04
River Rch & RM=1552,95,45540.53
 6910.1711556.3916110.4520402.3429787.42 31733.7
River Rch & RM=1552,95,45301.23
  6911.711559.29 16114.820408.2129795.99 31742.8
River Rch & RM=1552,95,45061.94
 6918.42   1157216133.87 20433.9 29833.531782.43
River Rch & RM=1552,95,44822.64
 6924.07 11582.816150.1820455.9929865.7431816.85
River Rch & RM=1552,95,44583.35
 6925.3311585.1516153.6820460.6729872.5831823.99
River Rch & RM=1552,95,44344.05
 6926.2511586.8716156.2320464.0929877.5731829.19
River Rch & RM=1552,95, 43656.3
 7634.4212799.7717874.7322669.0533096.8134845.94
River Rch & RM=1552,95,43512.36
 7651.4412831.3917921.7222731.8733188.5334939.87
River Rch & RM=1552,95,43175.19
 7653.8112835.9417928.6122741.2133202.1734954.26
River Rch & RM=1552,95,42692.83
 7658.2612844.4617941.4922758.6833227.6734981.16
River Rch & RM=1552,95,42258.19
 7692.29 12908.918038.2922889.2133418.2535179.86
River Rch & RM=1552,95,41823.56
 7694.8312913.7918045.72 22899.333432.9835195.46
River Rch & RM=1552,95,41388.92
 7705.9912935.4618078.6922944.2433498.5935265.33
River Rch & RM=1552,95,40954.29
 7712.8212948.81 18099.122972.1333539.3135308.96
River Rch & RM=1552,95,40519.65
 7716.4212955.8618109.8722986.8633560.8135332.02
River Rch & RM=1552,95,40085.02
 7719.1312961.1718117.9922997.9833577.0535349.47
River Rch & RM=1552,95,39728.45
 7839.3413192.9518469.64   2347634274.9636087.78
River Rch & RM=1552,95,39547.92
 7839.9113194.0818471.3623478.3734278.4236091.49
River Rch & RM=1552,95,39080.66
 7889.1113289.1918615.88 23675.134565.6436395.61
River Rch & RM=1552,95,38432.15
 7893.4813297.7818629.0623693.1634592.0236423.94
River Rch & RM=1552,95,37934.19
 7931.3213371.7418742.0923847.7534817.7136664.98
River Rch & RM=1552,95,37436.24
  7968.713443.9718851.8523997.1835035.8836895.59
River Rch & RM=1552,95,36938.28
 7982.2713470.63 18892.724053.1635117.6136983.15
River Rch & RM=1552,95,36440.32
 7986.7813479.5118906.3424071.8935144.9637012.52
River Rch & RM=1552,95,35942.36
 7996.9713499.7518937.5624114.8835207.7237080.41
River Rch & RM=1552,95,35444.41
 8046.5613595.2519082.4324311.8735495.3337383.17
River Rch & RM=1552,95,34946.45
 8053.8813609.8719105.0224343.0435540.8437432.52
River Rch & RM=1552,95,34448.49
 8058.8413619.6419120.0224363.6435570.92 37464.8
River Rch & RM=1552,95,33950.54
 8063.98 13629.919135.8924385.5535602.91 37499.5
River Rch & RM=1552,95,33452.58
 8067.9213637.8719148.2724402.7135627.9537526.88
River Rch & RM=1552,95,32954.62
 8180.9413852.3719471.2324839.24 36265.338187.88
River Rch & RM=1552,95,32456.66
 8317.5714108.5419854.43 25354.537017.5738957.21
River Rch & RM=1552,95,32264.38
 8318.3514110.1819857.0325358.1637022.9138963.21
River Rch & RM=1552,95,32135.95
 8319.2914112.1519860.1525362.5537029.3238970.41
River Rch & RM=1552,95,31844.11
 8320.7714115.2719865.09 25369.537039.48 38981.8
River Rch & RM=1552,95,31552.28
 8328.2314130.7719889.55 25403.837089.5539037.53
River Rch & RM=1552,95,31085.12
 8331.6614137.9819900.99 25419.937113.0639063.89
River Rch & RM=1552,95,30617.96
 8377.0914230.4220045.3125620.6937406.2139385.04
River Rch & RM=1552,95, 30150.8
 8390.0814257.9720089.1925682.6837496.7139487.08
River Rch & RM=1552,95,29683.64
  8394.214267.0820103.9925703.8737527.6539522.87
River Rch & RM=1552,95,29216.49
 8396.6714272.5520112.8725716.5937546.2139544.32
River Rch & RM=1552,95,28749.33
 8500.87   14474 20419.426134.6238156.5540184.92
River Rch & RM=1552,95,28282.17
 8505.1214483.2620434.33 26155.938187.6140220.45
River Rch & RM=1552,95,27815.01
 8508.69   14491 20446.826173.6538213.5340250.06
River Rch & RM=1552,95,27437.43
 8512.9514500.1920461.5726194.65 38244.240284.98
River Rch & RM=1552,95,27059.84
 8515.92 14506.620471.8526209.2638265.5240309.24
River Rch & RM=1552,95,26682.25
 8517.4914510.1420477.64 26217.6 38277.740323.44
River Rch & RM=1552,95, 26266.7
  8518.914513.34 20482.9 26225.2 38288.840336.45
River Rch & RM=1552,95,25851.14
 8520.9714518.0220490.5826236.2838304.9740355.38
River Rch & RM=1552,95,25435.58
 8522.5414521.6220496.5226244.8838317.5340370.16
River Rch & RM=1552,95,25020.03
 8523.7814524.4720501.2426251.7338327.5340381.99
River Rch & RM=1552,95,24604.47
 9992.7116897.4924099.0633496.3347216.66 67538.9
River Rch & RM=1552,95,24148.25
10003.4316912.7124117.7333518.5547247.9867562.78
River Rch & RM=1552,95,23692.02
10072.6717011.0424238.1833661.8947450.0367716.66
River Rch & RM=1552,95, 23235.8
10108.0217061.1924299.5733734.9147552.9667794.92
River Rch & RM=1552,95,22779.58
10148.2617118.26 24369.433817.94   4767067883.81
River Rch & RM=1552,95,22323.35
10235.12 17241.324519.85 33996.747921.9768074.86
River Rch & RM=1552,95,21867.13
10268.4217288.4424577.4534065.0948018.3968147.84
River Rch & RM=1552,95, 21410.9
10589.49 17741.625130.0734720.1348941.7368843.28
River Rch & RM=1552,95,20954.68
11101.1318459.2526001.1935748.5450391.38 69922.9
River Rch & RM=1552,95,20498.46
11113.9218477.1326022.8335774.0250427.3169949.46
River Rch & RM=1552,95, 19671.3
11384.3118854.1726478.5336309.9651182.7770506.16
River Rch & RM=1552,95,19149.81
11415.5718897.6726531.0236371.6151269.6670569.95
River Rch & RM=1552,95,18477.56
11865.4119521.5627282.0137251.7252510.2871475.17
River Rch & RM=1552,95,18239.76
11874.7919534.5227297.5837269.9352535.95 71493.8
River Rch & RM=1552,95,17375.79
14742.7723429.3431913.7442606.9560059.0576780.68
River Rch & RM=1552,95,16896.47
14897.0823635.2532154.6342882.2860447.1577044.77
River Rch & RM=1552,95,16393.79
14985.6423753.2732292.57 43039.8 60669.277195.52
River Rch & RM=1552,95,15782.79
15138.5123956.7532530.15 43310.961051.3477454.34
River Rch & RM=1552,95,14015.41
15714.4224720.3633419.2544322.9162477.8778413.91
River Rch & RM=1552,95,12589.49
16707.8526027.22   3493246035.9864892.64 80015.2
River Rch & RM=1552,95,9870.786
 17089.826526.3535506.9246684.2365806.4180613.88
River Rch & RM=1552,95,7779.149
17305.5226807.4635830.05 47047.966319.0580948.03
River Rch & RM=1552,95,4877.851
20451.4930847.3340423.7352169.3673538.2885531.95
River Rch & RM=1552,95,2776.769
21070.8431630.5241304.1853141.1574908.1386377.63
River Rch & RM=1552,95,1562.742
22285.9633156.5543010.9855016.6577551.8587989.57
River Rch & RM=1552,95,       0
22702.8133676.96 43590.555651.0178446.0488528.95
Boundary for River Rch & Prof#=1552,95,1
Up Type= 0
Dn Type= 2
Boundary for River Rch & Prof#=1552,95,2
Up Type= 0
Dn Type= 2
Boundary for River Rch & Prof#=1552,95,2
Up Type= 0
Dn Type= 2
Boundary for River Rch & Prof#=1552,95,2
Up Type= 0
Dn Type= 2
Boundary for River Rch & Prof#=1552,95,2
Up Type= 0
Dn Type= 2
Boundary for River Rch & Prof#=1552,95,2
Up Type= 0
Dn Type= 2

--- 1552_ras.g01 (geometry) ---

Geom Title=1552
Program Version=4.10

River Reach=1552,95
Reach XY= 30
532019.961123408742307.936023696532197.644085021 741342.57000402
533253.758594692741381.228953268533621.213241279740345.582754965
535246.864348173740260.991083869 535880.92632073 739216.63596184
534350.442737369736361.279801511533590.633339256737109.348518094
 531865.17185691736728.205483743530971.453494014737361.446049778
529081.889655886737243.108449829528663.748215736736842.224290649
529379.969882846736310.858508323528993.167659253735550.330054311
526342.536191108734951.941888787526162.353093474 733924.67849502
527195.109873979733454.444556509527380.257511407  732693.6676241
528455.418697597733470.948244821529280.406815707733232.994059801
 529251.18219879726951.276909734530651.388434468726013.727946767
531008.070710629724449.504326323533366.376546827724097.643797255
533601.742400588722885.699999772534818.852534294722006.741743732
534020.207494082721700.734263015534291.005215733720866.310897148
535958.161027161719922.034695203536899.727581709717158.860967734

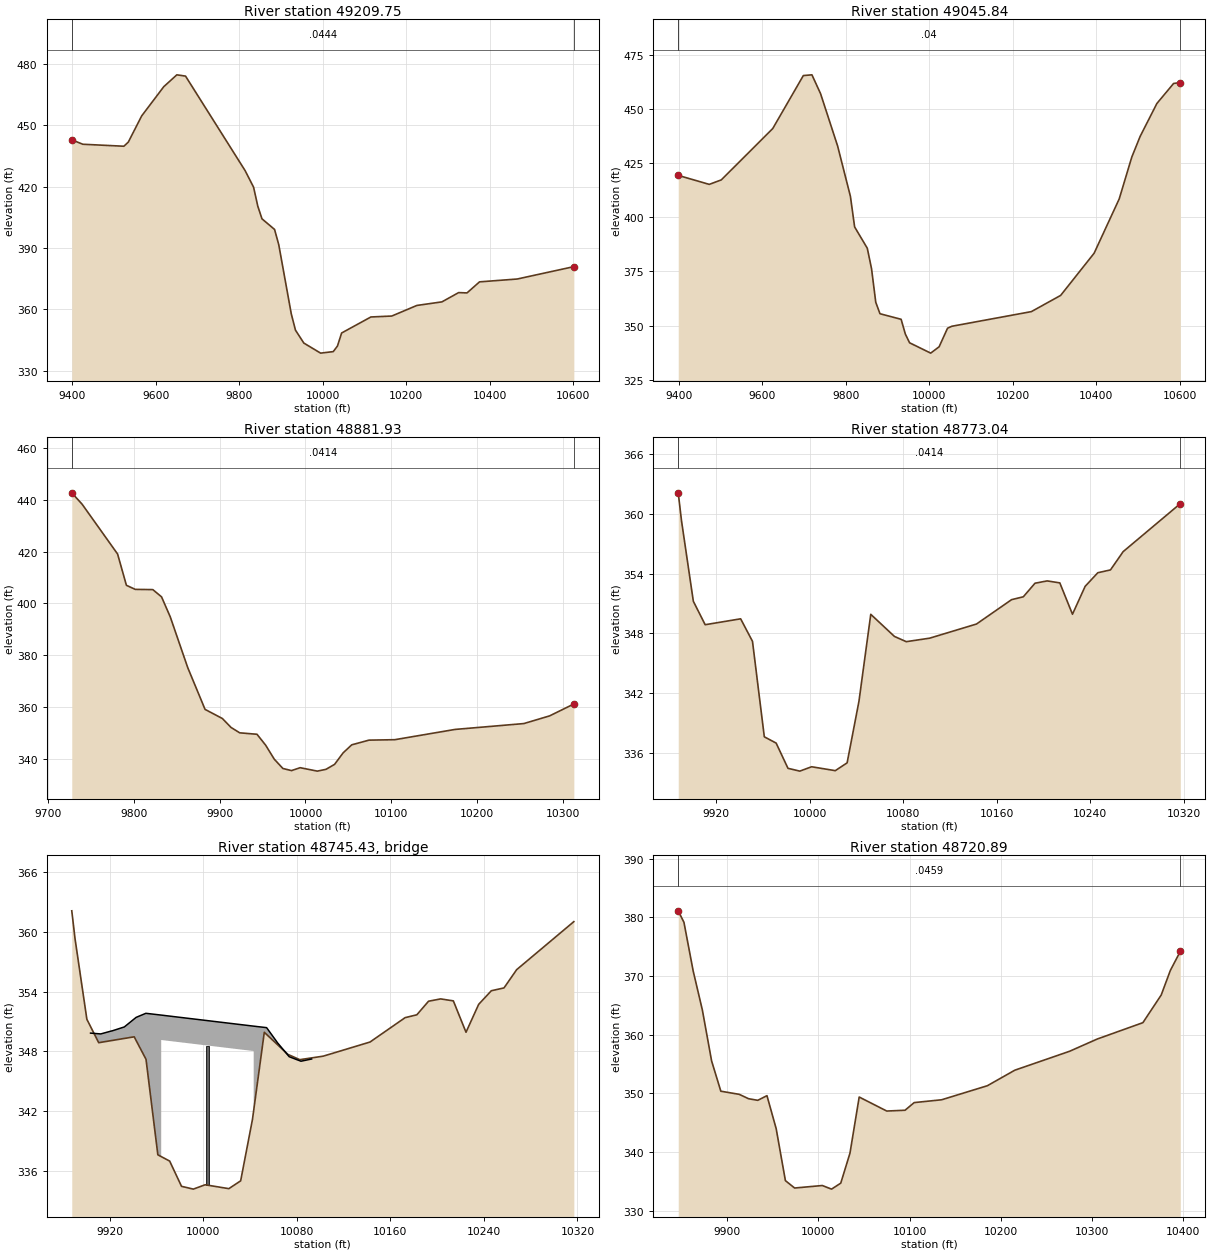
Type RM Length L Ch R = 1 ,49209.75,163.910500,163.910500,163.910500
XS GIS Cut Line= 6
532598.411093506742436.544738315 532413.63246394742358.426850714
532189.577809339742308.678559227532079.889835187742302.176466192
531851.300185093742313.897886313531419.512763674742296.479964376
#Sta/Elev= 30
9399.074442.82679425.453440.65819523.823439.6886 9534.48441.7276 9566.45454.5058
 9619.31468.77079650.599474.56569671.424473.93839814.163427.73479834.341419.6654
9844.383410.42569854.425 404.2319884.546399.04979894.551391.60889924.563357.8044
9934.567349.87159954.586343.55369994.756338.636710025.02339.376510035.04 342.077
10045.07348.468610115.11 356.29310165.12356.749610225.14361.919210285.17363.6676
10325.19368.1952 10345.2368.045610375.23373.445710465.33374.831110600.97380.8771
#Mann= 3 , 0 , 0
9399.074  0.0444       09399.074  0.0444       010600.97  0.0444       0
#XS Ineff= 2 , 0
       0                               0
Bank Sta=9399.074,10600.97
Exp/Cntr=0.3,0.1

Type RM Length L Ch R = 1 ,49045.84,163.910600,163.910600,163.910600
XS GIS Cut Line= 6
532600.290404149742312.903986418532419.048254137742226.989635221
532324.429127037742197.065272916532213.430242239742172.632506354
531933.015006431742132.793439243531428.959821652742103.395044901
#Sta/Elev= 30
9399.045419.41189473.304415.25319502.134417.32229625.312441.06849698.512465.5564
9719.108465.90059739.696457.24239780.594433.00149811.188409.75449821.319395.5843
9851.673385.71589861.791376.2922 9871.91360.74119882.028355.45039932.619352.8717
9942.737346.05399952.855342.022910003.44337.236410023.59340.175210043.73348.7506
10053.79349.6456 10244.4356.426210314.51363.916110394.63383.417210454.72408.5362
10484.77427.8358 10504.8437.430510544.86 452.63710584.92461.905210600.98462.3305
#Mann= 3 , 0 , 0
9399.045    0.04       09399.045    0.04       010600.98    0.04       0
#XS Ineff= 2 , 0
       0                               0
Bank Sta=9399.045,10600.98
Exp/Cntr=0.3,0.1

Type RM Length L Ch R = 1 ,48881.93,108.891300,108.891300,108.891300
XS GIS Cut Line= 6
532316.422587127742029.197836269532294.036461949742021.909352943
532234.120708287 742007.47729136532128.330162704741990.053297445
532049.816421926741981.574519917531736.863649845  741958.6809607
#Sta/Elev= 30
9727.619442.66969739.632438.29819781.029419.04549791.315406.96449801.601405.3955
9822.072405.30589832.248402.50779842.423394.7711 9862.75375.21779882.965359.0646
 9903.18355.53579913.287352.08039923.379 350.0149943.499349.45849953.559 345.259
 9963.62339.8545 9973.68336.2483 9983.74335.43229993.795336.553110013.86335.2281
10023.88335.919510033.91337.832410043.94342.303810053.96345.382710074.02347.1927
 10104.1347.362610174.28351.3229 10254.5353.587910284.58356.559210312.79 361.149
#Mann= 3 , 0 , 0
9727.619  0.0414       09727.619  0.0414       010312.79  0.0414       0
#XS Ineff= 2 , 0
       0                               0
Bank Sta=9727.619,10312.79
Exp/Cntr=0.3,0.1

Type RM Length L Ch R = 1 ,48773.04,52.153700,52.153700,52.153700
XS GIS Cut Line= 4
532167.770953059741889.748659387 531974.55595547741860.440766484
531859.495338917741856.098856434531749.862109959741901.688912034
#Sta/Elev= 30
9887.611362.10739890.414 359.2989900.528351.21859910.643348.86729940.986349.4586
  9951.1347.19739961.214337.61339971.329336.98369981.443 334.4519991.558334.1684
10001.67334.6072 10021.9334.214910032.02335.000810042.13341.174610052.24349.9104
10072.47 347.69110082.59347.164510102.61347.516310142.63348.935410172.66351.3842
10182.66351.668610192.67353.032210203.05353.264810213.88353.066510224.71349.9179
10235.54352.719610246.37 354.085 10257.2354.368410268.03356.202310316.91361.0216
#Mann= 3 , 0 , 0
9887.611  0.0414       09887.611  0.0414       010316.91  0.0414       0
#XS Ineff= 2 , 0
       0                               0
Bank Sta=9887.611,10316.91
Exp/Cntr=0.3,0.1

Type RM Length L Ch R = 3 ,48745.43,,,
BEGIN DESCRIPTION:
END DESCRIPTION:
Bridge Culvert--1,0,-1,-1, 0
Deck Dist Width WeirC Skew NumUp NumDn MinLoCord MaxHiCord MaxSubmerge Is_Ogee
10.000750,32.152200,2.6,0, 17, 17, , , 0.95, 0, 0,0,,
 9903.66 9912.39 9921.40 9922.47 9932.54 9942.62 9950.97 9964.09 9964.0910043.16
10043.1610054.2010062.2710063.5310073.5410083.5510092.68
  349.83  349.75  350.04  350.07  350.45  351.41  351.82  351.64  351.64  350.53
  350.53  350.38  349.07  348.86  347.46  347.01  347.23
 -650.17 -650.25 -649.96 -649.93 -649.55 -648.59 -648.18 -648.36  349.14  348.03
 -649.47 -649.62 -650.93 -651.14 -652.54 -652.99 -652.77
 9903.66 9912.39 9921.40 9922.47 9932.54 9942.62 9950.97 9962.10 9962.1010041.17
10041.1710054.2010062.2710063.5310073.5410083.5510092.68
  349.83  349.75  350.04  350.07  350.45  351.41  351.82  351.67  351.67  350.56
  350.56  350.38  349.07  348.86  347.46  347.01  347.23
 -650.17 -650.25 -649.96 -649.93 -649.55 -648.59 -648.18 -648.33  349.17  348.06
 -649.44 -649.62 -650.93 -651.14 -652.54 -652.99 -652.77
Pier Skew, UpSta & Num, DnSta & Num=  ,10003.62, 2 ,10001.64, 2 , 0 , 0 , 0 ,,
    3.00    3.00
 -648.91  351.09
    3.00    3.00
 -648.89  351.11
BR Coef=-1 , 0 , 0 ,, 0 ,,,0.8,0,1,0,
WSPro=,,,, 1 ,,,, 0 ,,,, 0 ,,,,-1 ,-1 ,-1 , 0 , 0 , 0 , 0 , 0
BC Design=,, 0 ,, 0 ,,,,,,

Type RM Length L Ch R = 1 ,48720.89,102.955000,102.955000,102.955000
XS GIS Cut Line= 3
532211.190053672741843.073126256532003.863848358741812.679755837
531664.109386295741788.799250528
#Sta/Elev= 30
9846.494381.1287 9852.75379.17289862.857370.87519872.963364.1867 9883.07355.5122
9893.177350.35589913.391349.81849923.498349.07789933.605 348.7989943.712349.5935
9953.819 343.9619963.925 335.0979974.032333.838910004.35334.264910014.46333.6501
10024.57334.667810034.67339.786610044.78349.362410074.95346.9718   10095347.1074
10105.02 348.41310135.09348.892810185.22351.290110215.29353.939710275.44357.1754
10305.51359.250710355.64362.048710375.69366.762710385.71370.955610396.63374.2115
#Mann= 3 , 0 , 0
9846.494  0.0459       09846.494  0.0459       010396.63  0.0459       0
#XS Ineff= 2 , 0
       0                               0
Bank Sta=9846.494,10396.63
Exp/Cntr=0.3,0.1

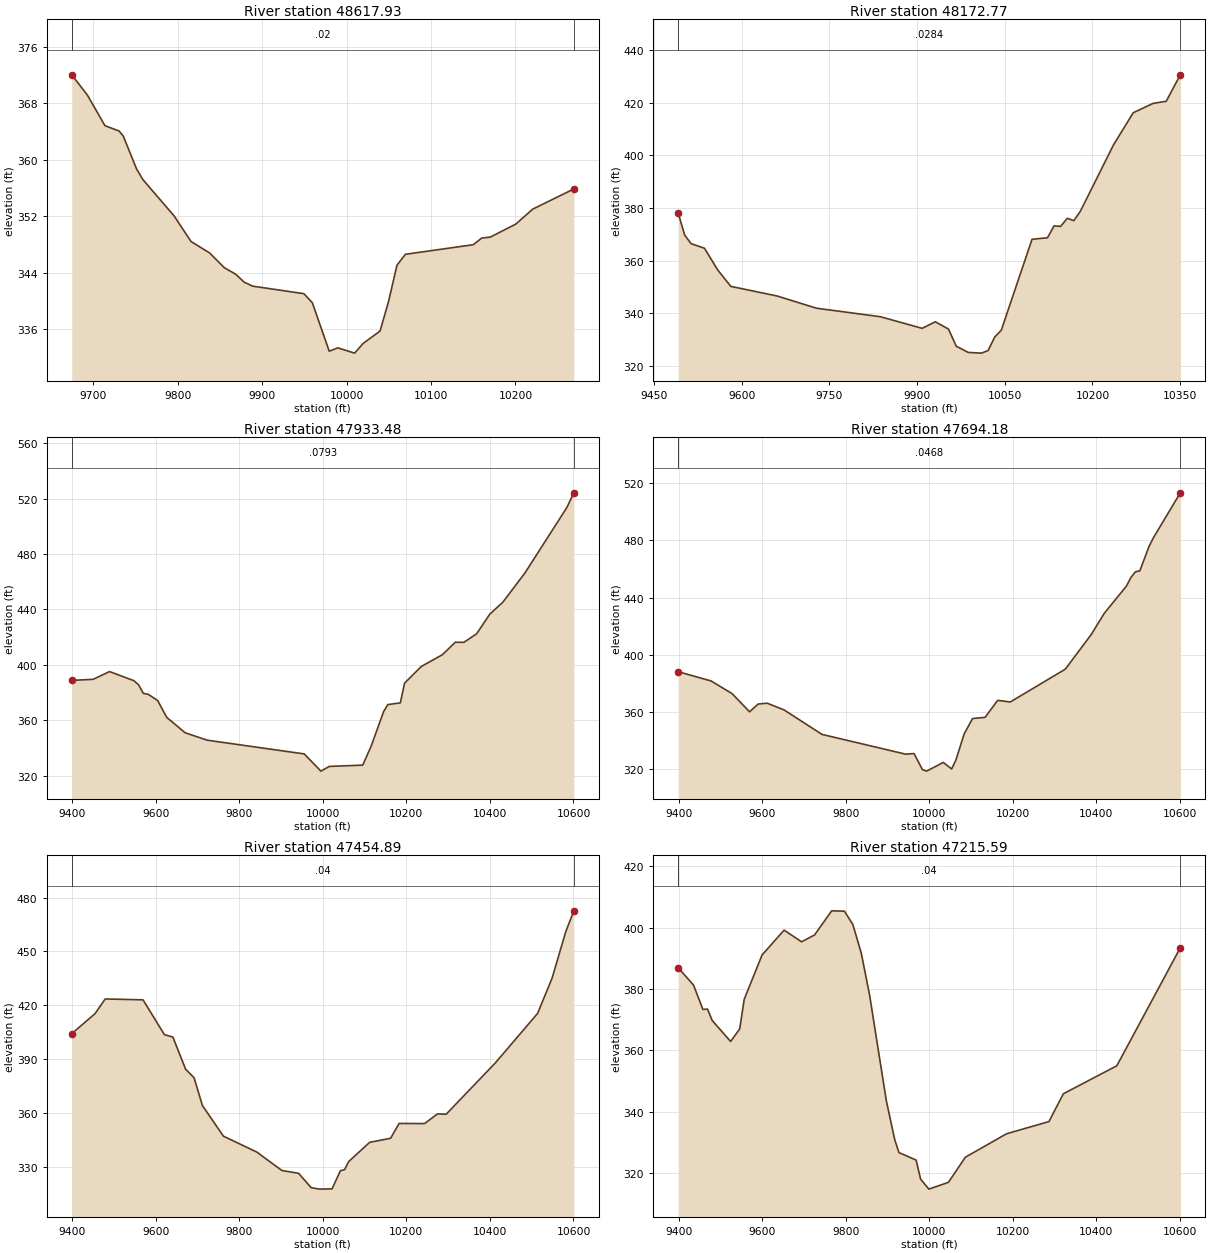
Type RM Length L Ch R = 1 ,48617.93,445.156800,445.156800,445.156800
XS GIS Cut Line= 6
532373.840537149741804.745849835532306.708160788741767.733712107
 532204.37387374741734.041307092532144.262913644741724.194752023
531943.347874552 741709.79081127531796.727294236741692.015635699
#Sta/Elev= 30
9674.527372.01779693.053369.1517 9713.85364.82269730.609364.0708  9735.5363.3556
9751.232358.71789758.889357.17879795.883352.03889815.766348.44189837.811346.8193
9855.335344.72169868.628343.81549878.761342.68459888.894 342.1239949.393341.0609
9959.424339.78769979.485 332.9219989.516333.393810009.57332.649310019.59334.0205
10039.64335.768110049.66339.929810059.68345.0834 10069.7346.631310150.03347.9852
 10160.1348.928810170.17349.060210200.38350.899410220.53 353.02210269.17355.8711
#Mann= 3 , 0 , 0
9674.527    0.02       09674.527    0.02       010269.17    0.02       0
#XS Ineff= 2 , 0
       0                               0
Bank Sta=9674.527,10269.17
Exp/Cntr=0.3,0.1

Type RM Length L Ch R = 1 ,48172.77,239.295000,239.295000,239.295000
XS GIS Cut Line= 2
532465.164484471741774.749484971 532067.56567657741013.631767079
#Sta/Elev= 30
9491.514378.00799502.514369.70499513.467 366.439 9536.36364.69899558.925356.4665
9581.489350.19379660.465346.55129728.158341.89219837.428338.65989908.674334.2527
9931.239336.73589953.803333.95979967.013327.4674 9987.65325.092310010.21324.8299
 10021.5325.809310032.78330.936910044.06 333.535 10096.6368.080810123.04368.6776
10134.32373.1824 10145.6373.003110156.88376.076910168.17375.166310179.45378.8077
10235.86403.917510269.71416.172210303.55419.727810326.12420.526210350.23430.5872
#Mann= 3 , 0 , 0
9491.514  0.0284       09491.514  0.0284       010350.23  0.0284       0
#XS Ineff= 2 , 0
       0                               0
Bank Sta=9491.514,10350.23
Exp/Cntr=0.3,0.1

Type RM Length L Ch R = 1 ,47933.48,239.295000,239.295000,239.295000
XS GIS Cut Line= 6
532633.594749348741920.493606584532529.082358704741749.196216246
532475.388382625741608.060568643532455.005860815741082.583571166
532415.334961138740928.359411501532348.568790521740779.939658028
#Sta/Elev= 30
9399.102388.69319450.315389.48439489.594395.0708 9547.54388.52219558.973385.5673
9570.406379.32149581.839378.69769604.513374.23119626.463361.9883 9670.33350.9018
 9723.11345.52039955.461 335.5949995.489323.1601 10015.5 326.56110095.55327.4973
10115.56341.056610145.57366.154410155.58  371.2210185.62372.463210195.63386.6622
10235.83 398.76810286.35407.270910317.03416.256910337.48416.180610368.25422.3542
10399.64436.529310431.04445.2214 10484.4466.564310584.01513.4826 10600.9524.1959
#Mann= 3 , 0 , 0
9399.102  0.0793       09399.102  0.0793       0 10600.9  0.0793       0
#XS Ineff= 2 , 0
       0                               0
Bank Sta=9399.102,10600.9
Exp/Cntr=0.3,0.1

Type RM Length L Ch R = 1 ,47694.18,239.295000,239.295000,239.295000
XS GIS Cut Line= 6
532806.609666108  741934.2050765532747.845406122741784.602269544
532717.899434301741648.792245821532677.322935638741049.135616277
532641.159621139740914.837443813532577.037774505740767.426308173
#Sta/Elev= 30
9399.064388.09349477.558381.65339527.998 372.7629569.866360.07149590.507365.5132
9611.911366.08489652.175 361.4169743.199344.25379943.555330.42319963.558330.8437
9983.562319.65529993.563318.562610033.57324.650610053.57 320.07510063.57326.2099
 10083.6344.615510103.62355.351410133.65356.174910163.76368.0855 10193.9366.9243
10325.63389.878610387.62414.070610418.97428.960210471.85447.925910482.51453.9134
10493.34457.948510504.19458.716610525.88475.630210536.85481.944910600.93513.2225
#Mann= 3 , 0 , 0
9399.064  0.0468       09399.064  0.0468       010600.93  0.0468       0
#XS Ineff= 2 , 0
       0                               0
Bank Sta=9399.064,10600.93
Exp/Cntr=0.3,0.1

Type RM Length L Ch R = 1 ,47454.89,239.295000,239.295000,239.295000
XS GIS Cut Line= 6
533023.237986912741936.932037699532980.058487797741814.851219778
532947.514804673 741651.71404254532924.235051947 741121.82636587
532870.776810178740956.745251569532774.853316026740780.527788659
#Sta/Elev= 30
 9399.08404.13179454.579415.23379479.143423.47799569.669 422.9829620.881403.5796
 9641.14402.24579671.528 384.3569691.787379.58099711.904364.07929762.066347.0261
9842.114 338.1559902.116327.88539942.117326.32199972.117318.33079992.118317.5139
10022.12317.674610042.13327.785510052.13328.360210062.13332.928210112.19343.5855
10162.36345.849410182.55354.101410243.66354.042710274.63359.436310295.27359.2337
10413.16387.887510514.11415.402810548.81435.046910581.42460.8595 10600.9472.5751
#Mann= 3 , 0 , 0
 9399.08    0.04       0 9399.08    0.04       0 10600.9    0.04       0
#XS Ineff= 2 , 0
       0                               0
Bank Sta=9399.08,10600.9
Exp/Cntr=0.3,0.1

Type RM Length L Ch R = 1 ,47215.59,239.295000,239.295000,239.295000
XS GIS Cut Line= 6
533286.136590021741958.081488178533153.225248742741585.426190818
533147.947453986741461.577020137533186.138775171 741303.64108585
 533073.42652941741078.710208059532927.658521868740862.006263886
#Sta/Elev= 30
9399.154386.89739435.958381.21269458.209373.32639469.334373.44319480.459369.7274
9524.551362.88839546.299366.98129557.041376.60889599.799391.06089652.569399.1606
 9694.36395.34989725.454397.59059766.431405.44419796.913405.33919817.084400.9957
9837.205391.68899857.256377.93229897.297343.52559917.307330.92679927.398326.7025
9968.474324.26749979.358318.0392    9999314.801110045.82317.012910086.37325.1949
10185.06332.835710286.51336.8055 10320.9 345.85110448.93354.980210600.84393.4228
#Mann= 3 , 0 , 0
9399.154    0.04       09399.154    0.04       010600.84    0.04       0
#XS Ineff= 2 , 0
       0                               0
Bank Sta=9399.154,10600.84
Exp/Cntr=0.3,0.1

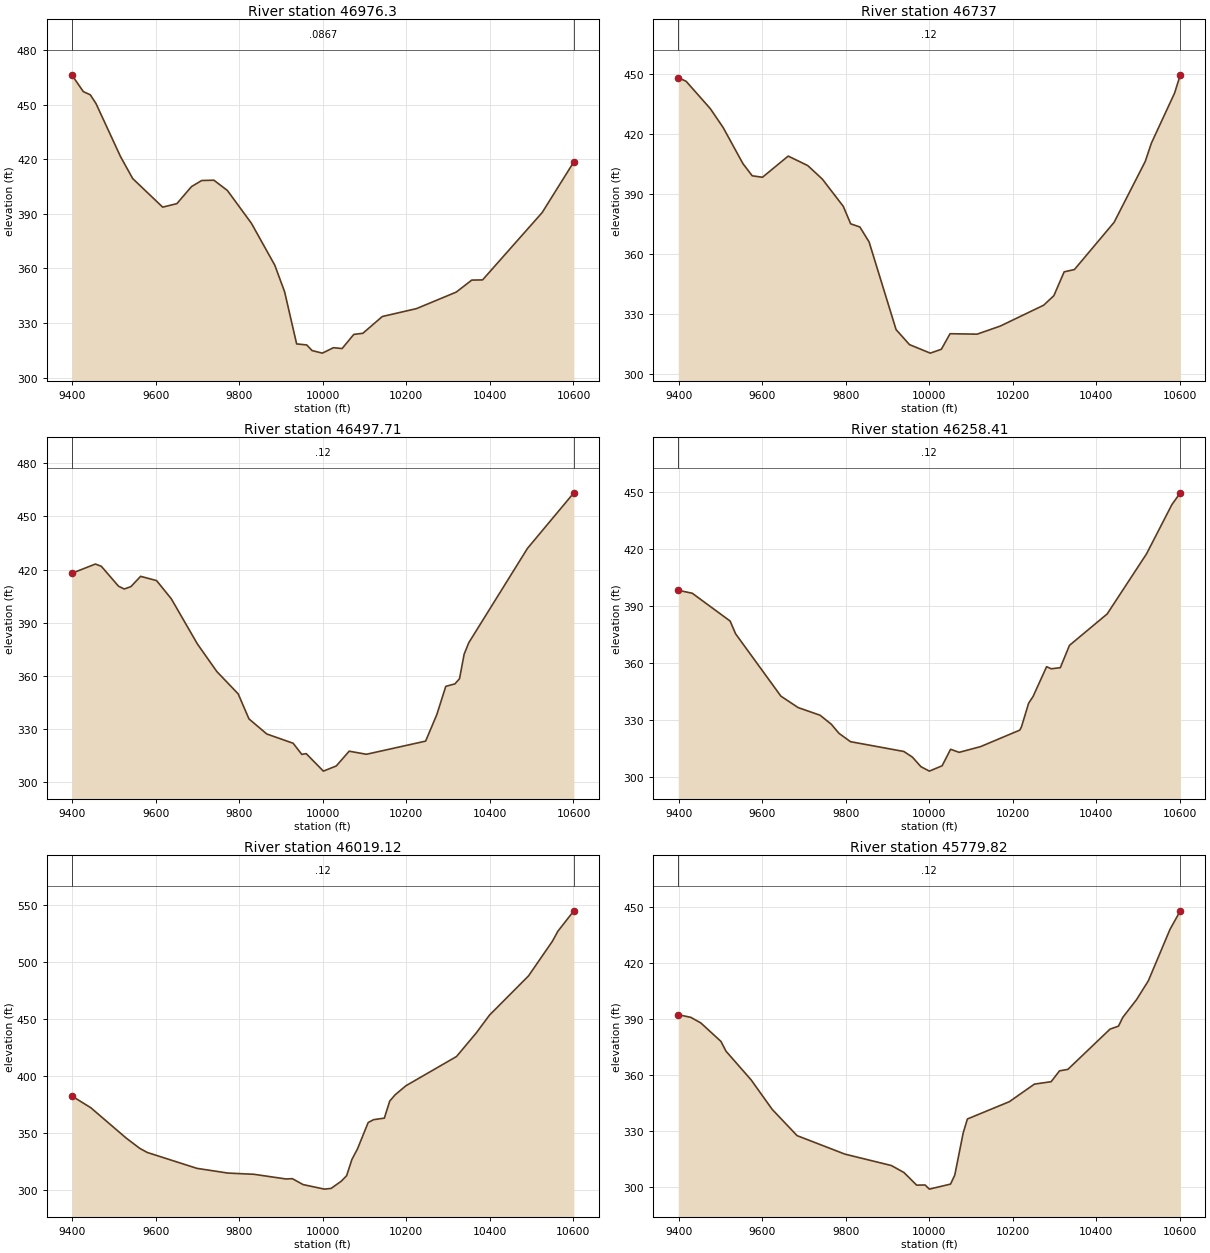
Type RM Length L Ch R = 1 , 46976.3,239.295000,239.295000,239.295000
XS GIS Cut Line= 6
533743.466516225741648.090570786533517.836002873741416.631584229
533311.914747974741265.609469765533283.197137338741217.831897162
533130.951825656741067.137250726532905.684566194 740796.48963057
#Sta/Elev= 30
9399.122466.53759426.879457.27329443.444455.55689456.942450.81459515.884421.5285
9544.968409.4774 9616.76393.74759650.768395.67919685.721405.05159710.196408.4011
9739.362 408.5629771.673402.89999829.025384.90849885.107361.8047 9908.59347.1918
9937.407318.50229961.582317.93939974.328314.8415    9999313.433210025.48316.4195
10046.21 315.95510074.21 323.72810095.94324.357910142.45333.584910224.28337.9215
10319.41347.0086 10356.5353.604410382.43353.715310525.04390.7522 10600.9418.6577
#Mann= 3 , 0 , 0
9399.122  0.0867       09399.122  0.0867       0 10600.9  0.0867       0
#XS Ineff= 2 , 0
       0                               0
Bank Sta=9399.122,10600.9
Exp/Cntr=0.3,0.1

Type RM Length L Ch R = 1 ,   46737,239.295000,239.295000,239.295000
XS GIS Cut Line= 6
 533918.94625752741357.008171135533792.834577386741247.005700275
533650.067531241741151.309362774533292.373593277740997.531291059
533165.053812389740927.497209833532915.176508986740716.863425977
#Sta/Elev= 30
9399.081448.31889418.007446.48799476.012432.77989506.686423.34599553.905405.3564
9576.129399.25219600.741398.52299662.272409.10459709.224404.35219744.218397.5593
9794.235383.96019811.847375.24339833.896373.66749855.945366.19989920.572322.3568
9952.721314.862210002.39310.615410028.89312.538510049.74320.314410114.54 320.099
10170.02324.147910273.66334.549510298.26339.337510322.86351.244510347.46352.3981
10442.38375.976610516.84406.366710531.73415.599410587.23440.625510600.91449.7207
#Mann= 3 , 0 , 0
9399.081    0.12       09399.081    0.12       010600.91    0.12       0
#XS Ineff= 2 , 0
       0                               0
Bank Sta=9399.081,10600.91
Exp/Cntr=0.3,0.1

Type RM Length L Ch R = 1 ,46497.71,239.295000,239.295000,239.295000
XS GIS Cut Line= 6
534004.833092819741123.016276952 533855.77595901740985.553796257
533730.635646063740904.690744962533598.764686002740850.509285221
533208.942063485740735.143371711532952.236704674740581.294857166
#Sta/Elev= 30
9399.116417.89649455.621423.11899469.806421.87599511.184410.60279524.805409.0441
9540.593410.3818 9563.94416.1934 9602.05413.79349637.251 403.5699699.693378.1064
9746.129 362.5619797.508349.88399823.323335.77479865.942327.27139929.042322.0433
9949.745315.7651 9960.25316.198110001.41306.325310032.27309.240310063.12317.5699
10104.51315.831110246.13323.246610272.92338.213110294.38354.132410316.25355.5234
10327.27358.4748 10338.3372.234710349.32378.698210489.97431.980510600.93463.2927
#Mann= 3 , 0 , 0
9399.116    0.12       09399.116    0.12       010600.93    0.12       0
#XS Ineff= 2 , 0
       0                               0
Bank Sta=9399.116,10600.93
Exp/Cntr=0.3,0.1

Type RM Length L Ch R = 1 ,46258.41,239.295100,239.295100,239.295100
XS GIS Cut Line= 6
534004.065918246740931.209794119533827.258311789740727.243386118
533713.810833385740639.790757508533282.637789545 740521.15424659
533139.884390308740452.375000094532988.519654036740353.681816139
#Sta/Elev= 30
9399.111398.12849432.772396.56029523.347381.96189536.468375.25129644.825342.5312
9686.016336.53449738.747332.48869765.612327.75679783.779323.01099811.447318.6156
9939.263313.45679959.699310.47869980.009305.493310000.31303.143710030.75305.9554
10051.05314.622710071.44313.011410122.62316.003910216.57324.671310220.68 326.375
10237.82 338.80510248.45 342.33710280.88357.994910291.82356.892710313.69357.4774
10335.56369.183110425.87 385.70110520.04417.245510580.87443.164310600.92449.3063
#Mann= 3 , 0 , 0
9399.111    0.12       09399.111    0.12       010600.92    0.12       0
#XS Ineff= 2 , 0
       0                               0
Bank Sta=9399.111,10600.92
Exp/Cntr=0.3,0.1

Type RM Length L Ch R = 1 ,46019.12,239.295000,239.295000,239.295000
XS GIS Cut Line= 6
533961.901090081740836.543510618533728.475729587 740517.69713987
533681.474923125740455.893493454 533607.01189353740370.951503948
533327.325885678740028.455871258533214.725514257739895.804228536
#Sta/Elev= 30
9399.033382.22889444.573371.90679529.216345.2606 9562.06336.13829580.002332.5705
9698.503318.64669772.747314.4938 9835.27313.41659911.999309.29599927.169309.5683
9952.816304.368410003.96300.382410019.77301.009610044.02307.281610056.93312.1286
10069.85326.593210082.98335.707410108.59358.8859 10121.5361.397510147.33362.7459
10160.25 377.76310173.16383.261310198.99391.213110320.03416.869410367.44437.6346
10399.05  453.2510492.39487.686810549.57518.110310562.68526.904510600.98 544.886
#Mann= 3 , 0 , 0
9399.033    0.12       09399.033    0.12       010600.98    0.12       0
#XS Ineff= 2 , 0
       0                               0
Bank Sta=9399.033,10600.98
Exp/Cntr=0.3,0.1

Type RM Length L Ch R = 1 ,45779.82,239.295000,239.295000,239.295000
XS GIS Cut Line= 6
534028.183486232 740899.86456745 533881.75012023740673.027248945
533822.975189403740524.267763134 533852.52704823740101.330394179
533838.989124962739947.128005325533798.732774678739760.832744901
#Sta/Elev= 30
9399.123392.41669429.093391.0042  9453.2388.00489501.413378.10949513.466372.8828
9573.552357.54559624.083341.73459683.603327.69929798.132317.79629909.346311.6983
9939.502307.95029969.794301.20339990.066301.283210000.21299.070110050.93301.7641
10061.07  306.5710081.22329.1567 10091.3336.606610191.68345.861510251.69355.2636
10291.75356.565510311.79362.363410331.83363.160910432.69384.693410453.01386.3051
10463.16 390.96510496.16400.4714 10524.5410.598410576.02437.988110600.92447.9964
#Mann= 3 , 0 , 0
9399.123    0.12       09399.123    0.12       010600.92    0.12       0
#XS Ineff= 2 , 0
       0                               0
Bank Sta=9399.123,10600.92
Exp/Cntr=0.3,0.1

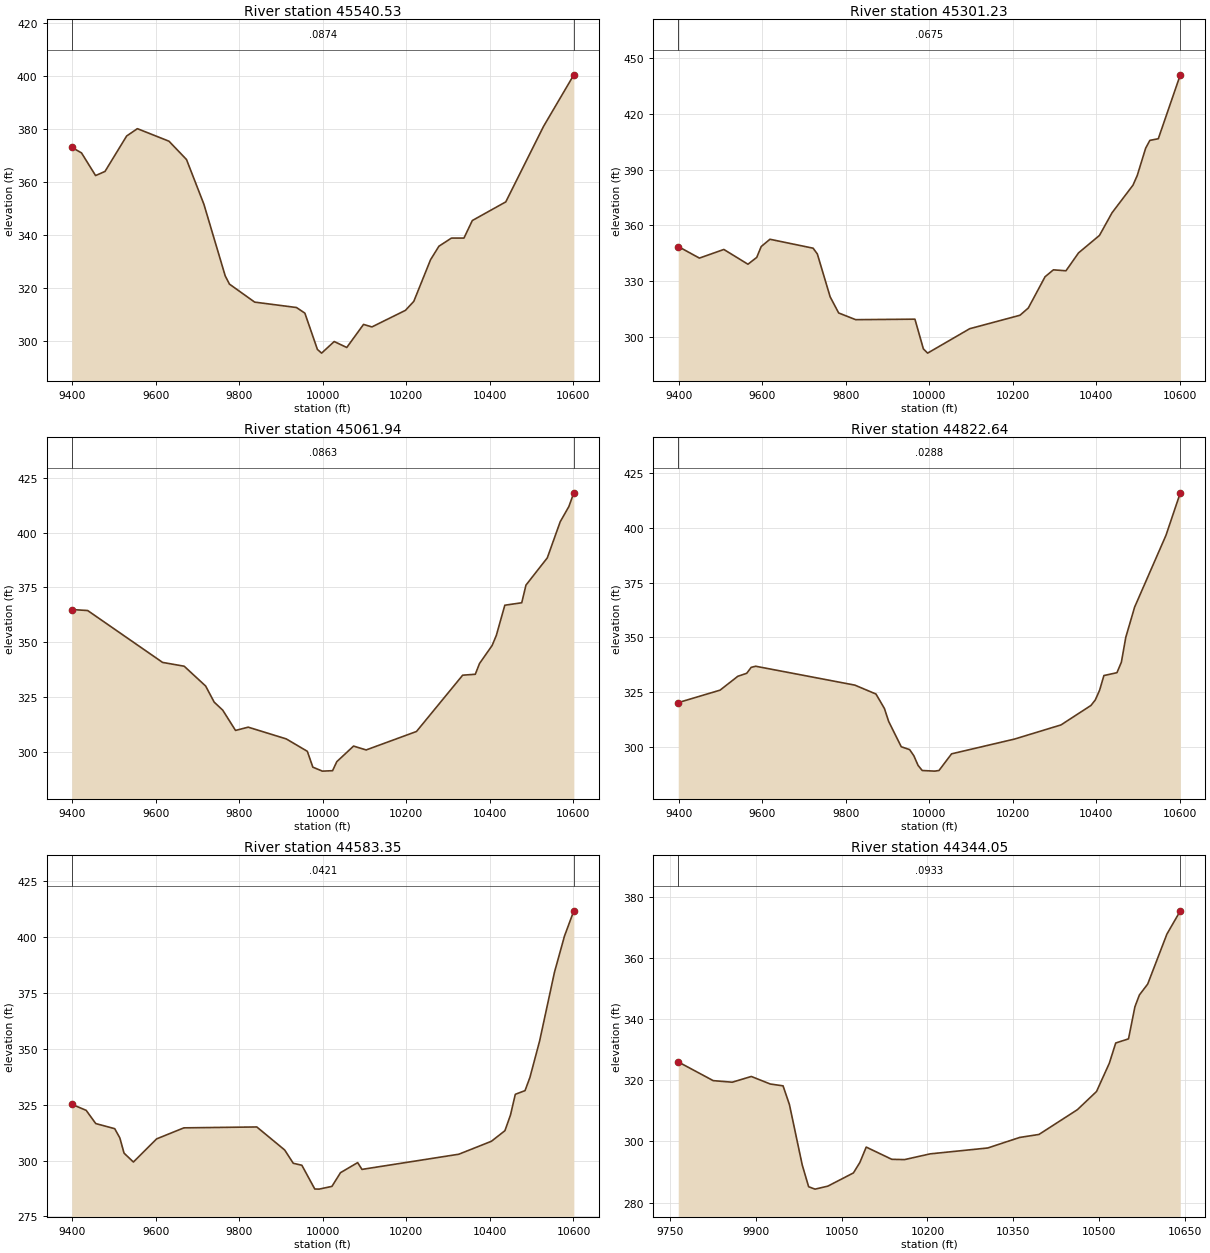
Type RM Length L Ch R = 1 ,45540.53,239.295000,239.295000,239.295000
XS GIS Cut Line= 6
534204.459950469740965.742710355534117.232252852740784.329348015
 534067.47344844740597.593658698 534061.71750961740464.825529549
534085.945057339740062.037009817534064.194909788739793.107250566
#Sta/Elev= 30
9399.096373.16559422.409371.06059456.127362.51279478.605 364.0739530.472377.4401
9556.193380.19929631.788375.47329673.752368.56989715.311351.75129766.434324.7015
9776.565321.59629836.953314.81019937.051312.77359957.084 310.6579987.149 296.966
9997.188295.5804 10027.3299.9515 10057.4297.708610097.54306.405610117.61305.4577
10197.86311.709910217.88315.103510257.91330.780910277.91 335.87110307.91338.9486
10337.92338.957110357.92345.563810438.01 352.59410528.34381.036210600.96400.4965
#Mann= 3 , 0 , 0
9399.096  0.0874       09399.096  0.0874       010600.96  0.0874       0
#XS Ineff= 2 , 0
       0                               0
Bank Sta=9399.096,10600.96
Exp/Cntr=0.3,0.1

Type RM Length L Ch R = 1 ,45301.23,239.295000,239.295000,239.295000
XS GIS Cut Line= 6
534454.016880097 740960.99378743534377.660173879740752.647398717
534330.812565928740546.586732672534295.723160808740308.883752523
534271.077477708739942.449760297534250.052077897739782.983527631
#Sta/Elev= 30
9399.068 348.6619449.754342.45119508.262347.0894 9565.95339.15429587.013342.8267
9597.684348.65579618.607352.56329721.893347.76949732.095344.67079762.699321.6684
9783.102312.98759823.908309.39119965.676309.65349985.919 293.7079996.041291.4246
10096.76304.530210217.07311.755210237.11 315.64510277.17332.4162 10297.2336.1487
10327.25335.6375 10357.3345.237810407.44354.624610437.52366.776910487.82381.6507
10497.88386.8056   10518401.453710528.06405.645510548.29406.545610600.97440.8511
#Mann= 3 , 0 , 0
9399.068  0.0675       09399.068  0.0675       010600.97  0.0675       0
#XS Ineff= 2 , 0
       0                               0
Bank Sta=9399.068,10600.97
Exp/Cntr=0.3,0.1

Type RM Length L Ch R = 1 ,45061.94,239.295000,239.295000,239.295000
XS GIS Cut Line= 6
534682.282658683 740930.52182546534614.383284683740735.437291255
 534573.42808057740562.217900217534541.057390116740340.722862796
534502.435829199739950.113301959534462.695310761739753.433237963
#Sta/Elev= 30
9399.051364.92129437.077364.47689616.481340.81179668.154339.0857 9719.55330.0419
9739.997322.70269760.445319.05159791.055309.80129821.476 311.2929912.578305.9362
9962.993300.27229976.177293.0548    9999291.248610023.42291.449610033.46295.5491
10073.63302.668210103.76300.903110224.27309.324910334.83334.994710365.04335.4071
10375.11340.300710405.34348.535110415.47353.172610435.73 366.88810476.24368.0148
10486.38376.074610537.45388.4914 10568.4404.980610589.04411.879310600.97418.1376
#Mann= 3 , 0 , 0
9399.051  0.0863       09399.051  0.0863       010600.97  0.0863       0
#XS Ineff= 2 , 0
       09469.532                       0
Bank Sta=9399.051,10600.97
Exp/Cntr=0.3,0.1

Type RM Length L Ch R = 1 ,44822.64,239.295000,239.295000,239.295000
XS GIS Cut Line= 6
534927.820925682 740907.43542572534858.067450287740728.897803646
534815.349626947740574.108445851534749.553815851740029.073080183
 534717.54277682739893.689272715534660.311439273739743.468193813
#Sta/Elev= 30
9399.056320.22349499.142325.92059541.725332.26339563.016333.62829573.661336.3372
9584.307336.8531 9821.89328.21829872.449324.14489892.667317.52479902.776311.6248
9932.944300.04939953.048298.73359963.099295.93169973.147291.53799983.178289.1912
10013.27288.9083 10023.3289.207210053.39296.812610203.98303.557510315.25310.0244
   10387318.924610397.34321.430210407.68 325.86110418.02332.596310449.25333.9042
10459.83338.6888 10470.4350.077810491.55363.881310566.58396.678210600.93416.1189
#Mann= 3 , 0 , 0
9399.056  0.0288       09399.056  0.0288       010600.93  0.0288       0
#XS Ineff= 2 , 0
       09619.936                       0
Bank Sta=9399.056,10600.93
Exp/Cntr=0.3,0.1

Type RM Length L Ch R = 1 ,44583.35,239.295000,239.295000,239.295000
XS GIS Cut Line= 6
535230.032310504 740855.06303993535139.732910385740683.110354299
535082.118866295740539.485667113534945.847335124740032.412980842
534873.079317951739882.841184743534788.005000726 739746.32703605
#Sta/Elev= 30
9399.043325.21229433.522322.48939456.459316.57159501.873314.28249514.105 310.151
9524.208303.33639546.544 299.3639602.145309.71329667.401314.65089841.981315.0495
 9908.72304.74829929.292298.79379949.864297.90979980.722287.29179991.008287.2276
10021.83 288.45410042.37294.596710083.43299.0949 10093.7296.058810325.61302.8501
10403.62308.646610435.94313.383910449.17320.348510460.81329.6655 10484.1331.3222
10495.74337.186810519.03353.552510554.59384.324210578.56400.512610600.93411.7837
#Mann= 3 , 0 , 0
9399.043  0.0421       09399.043  0.0421       010600.93  0.0421       0
#XS Ineff= 2 , 0
       09788.017                       0
Bank Sta=9399.043,10600.93
Exp/Cntr=0.3,0.1

Type RM Length L Ch R = 1 ,44344.05,687.754000,687.754000,687.754000
XS GIS Cut Line= 3
535355.796561152740470.084222764535278.192379534740309.869138137
534962.768931687739684.028963789
#Sta/Elev= 30
9763.692325.99029824.898319.87149858.232319.35829891.566321.2337  9924.9318.7671
9947.165318.17399958.363312.0469 9980.76292.32369991.958285.225210003.16284.4441
10025.55285.418910070.35289.735910081.54293.116510092.74298.169610137.54294.1784
10159.93294.088410204.73295.960710305.51297.8801 10361.5301.3285 10395.1302.2967
10462.29310.372710495.88316.320310518.28325.553410529.48332.162510551.87333.5149
10563.07343.982510570.93347.849810585.47351.410710619.06367.712610642.55 375.327
#Mann= 3 , 0 , 0
9763.692  0.0933       09763.692  0.0933       010642.55  0.0933       0
#XS Ineff= 2 , 0
       09897.387                       0
Bank Sta=9763.692,10642.55
Exp/Cntr=0.3,0.1

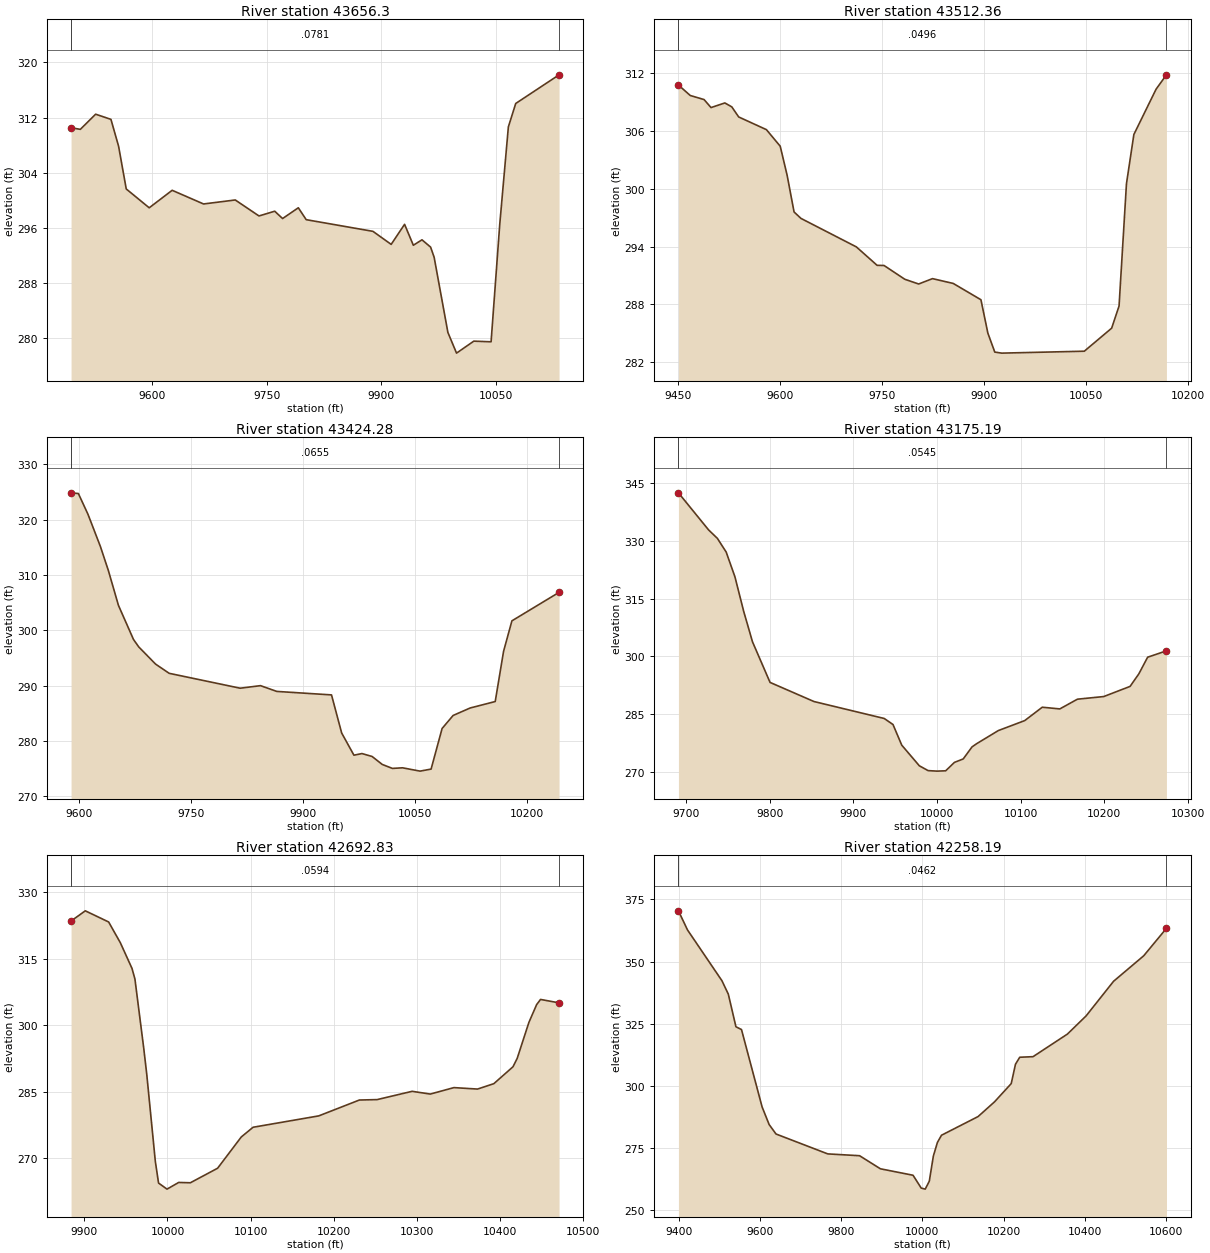
Type RM Length L Ch R = 1 , 43656.3,143.936500,143.936500,143.936500
XS GIS Cut Line= 6
535465.944431841740117.110364407535455.930989057739974.418804675
535503.494842291739794.176834464535528.528449297739721.579374224
535548.555334866739686.532324478535458.434349775739516.303797051
#Sta/Elev= 30
9493.609310.53689505.749 310.2979525.799312.49669545.848 311.7479555.872307.8495
9565.897301.65019595.971298.91889626.044301.45599667.184299.47349708.699300.0535
9739.769297.73379760.384 298.4239770.692297.35899791.308298.92169801.616297.1961
9889.048295.50279912.916293.61199930.485296.52049941.971 293.4859953.286294.2748
9964.601293.21139969.209291.74869987.231280.83599998.546277.836310021.18279.5748
10043.81279.478810055.12296.467610066.44310.649410076.07314.049610132.85318.2079
#Mann= 3 , 0 , 0
9493.609  0.0781       09493.609  0.0781       010132.85  0.0781       0
#XS Ineff= 2 , 0
       0 9942.33                       0
Bank Sta=9493.609,10132.85
Exp/Cntr=0.3,0.1

Type RM Length L Ch R = 1 ,43512.36,88.085300,88.085300,88.085300
XS GIS Cut Line= 4
535721.287222981740082.063314661535631.166237861739593.907978654
535616.146073699739488.766829357535511.004924387739443.706336811
#Sta/Elev= 30
  9450.9310.73769468.251309.65639488.589309.23299498.758 308.4039519.096308.8837
9529.265308.47919539.434307.4303 9580.11306.11879600.448304.39839610.617301.3784
9620.786297.58559630.955296.91539712.307293.96469742.814292.05269752.983 292.037
 9783.49290.60859803.828290.11839824.166290.67389854.673290.17579895.349288.4876
9905.518285.03019915.687283.06149925.856282.953410047.22283.1522 10087.4285.5381
10098.28287.836210109.16300.508310120.04305.613410152.68310.3085 10167.9 311.798
#Mann= 3 , 0 , 0
  9450.9  0.0496       0  9450.9  0.0496       0 10167.9  0.0496       0
#XS Ineff= 2 , 0
       09890.812                       0
Bank Sta=9450.9,10167.9
Exp/Cntr=0.3,0.1

Type RM Length L Ch R = 1 ,43424.28,249.091500,249.091500,249.091500
XS GIS Cut Line= 3
535981.636735529 739811.70035933 535633.66959855739433.692894027
535508.501563698739371.108876586
#Sta/Elev= 30
9589.142324.82969598.941324.70199611.841320.93919628.471315.11869639.024310.8292
9652.616304.49129672.767298.3333  9679.8296.98659702.297 293.8859720.575292.2119
9815.718289.52169842.901289.98299864.715 288.9419938.044288.31179951.636281.4276
9968.071277.4171 9978.82  277.719992.411277.1825   10006275.7453 10019.6275.0284
10033.19275.135410056.66274.536410071.43274.905610086.19282.244710100.96284.5968
 10123.8285.947410157.34287.112910168.52 296.184 10179.7 301.69510242.86306.8435
#Mann= 3 , 0 , 0
9589.142  0.0655       09589.142  0.0655       010242.86  0.0655       0
#XS Ineff= 2 , 0
       09865.371                       0
Bank Sta=9589.142,10242.86
Exp/Cntr=0.3,0.1

Type RM Length L Ch R = 1 ,43175.19,482.359200,482.359200,482.359200
XS GIS Cut Line= 2
536129.335016668739393.639122859535573.588941842739215.900513351
#Sta/Elev= 30
9691.016 342.5039727.064332.87369737.563330.67979748.062327.13649758.561320.6919
 9769.06311.70649779.559303.81259800.557293.26829853.052288.30369937.044283.9028
9947.543282.33349958.041 276.9679979.039271.61739989.538270.361110000.04270.2288
10010.54270.312910021.04272.502410031.53273.392110042.03276.518510047.65277.3662
10073.53280.764110105.03283.349910126.03286.825910147.02286.384810168.02 288.909
10199.52 289.59510231.01292.231510241.51295.492410252.01299.811710274.49301.4669
#Mann= 3 , 0 , 0
9691.016  0.0545       09691.016  0.0545       010274.49  0.0545       0
#XS Ineff= 2 , 0
       0                               0
Bank Sta=9691.016,10274.49
Exp/Cntr=0.3,0.1

Type RM Length L Ch R = 1 ,42692.83,434.634900,434.634900,434.634900
XS GIS Cut Line= 2
535919.052718073738772.805669904535505.998203009 739190.86690639
#Sta/Elev= 30
9883.869323.45889901.011325.75419929.127323.24269943.185318.57529957.242312.7863
9960.776310.3973  9971.3294.92719975.004288.96159985.358269.29439989.232264.4145
9999.415 263.04610013.47264.551310027.53264.476810060.37267.756410088.83274.7912
10103.06276.986210182.17279.548310231.11283.123410252.45283.217310294.63285.0844
10316.48284.464110344.93285.920310373.39285.592710393.03286.809610416.08290.6129
10421.15292.5075 10435.2300.591410444.53 304.61310449.26305.789510471.57305.0173
#Mann= 3 , 0 , 0
9883.869  0.0594       09883.869  0.0594       010471.57  0.0594       0
#XS Ineff= 2 , 0
       0                               0
Bank Sta=9883.869,10471.57
Exp/Cntr=0.3,0.1

Type RM Length L Ch R = 1 ,42258.19,434.634900,434.634900,434.634900
XS GIS Cut Line= 6
535687.180389702738368.996235557535438.428967066738735.956619962
535413.671002039739054.831204704 535371.55271778739174.961166829
535270.313084423739264.342428385 535111.12707654 739320.37898502
#Sta/Elev= 30
9399.133370.35879421.332362.71029506.251 342.2799521.979336.88119540.737323.7794
9554.409322.65959605.129291.5875 9622.45284.50539639.464280.69139766.834272.7042
 9845.19271.97239896.514266.71819976.924264.11929996.929258.983110006.93258.5488
10016.93261.743210026.94271.852610036.94277.319110046.94280.197310137.06287.7022
10177.45293.600310218.68300.945310229.15308.717910239.62311.534610272.35311.7603
10357.02 320.83410403.01  328.1310470.74342.058110544.94352.293110600.92363.3196
#Mann= 3 , 0 , 0
9399.133  0.0462       09399.133  0.0462       010600.92  0.0462       0
#XS Ineff= 2 , 0
       0                               0
Bank Sta=9399.133,10600.92
Exp/Cntr=0.3,0.1