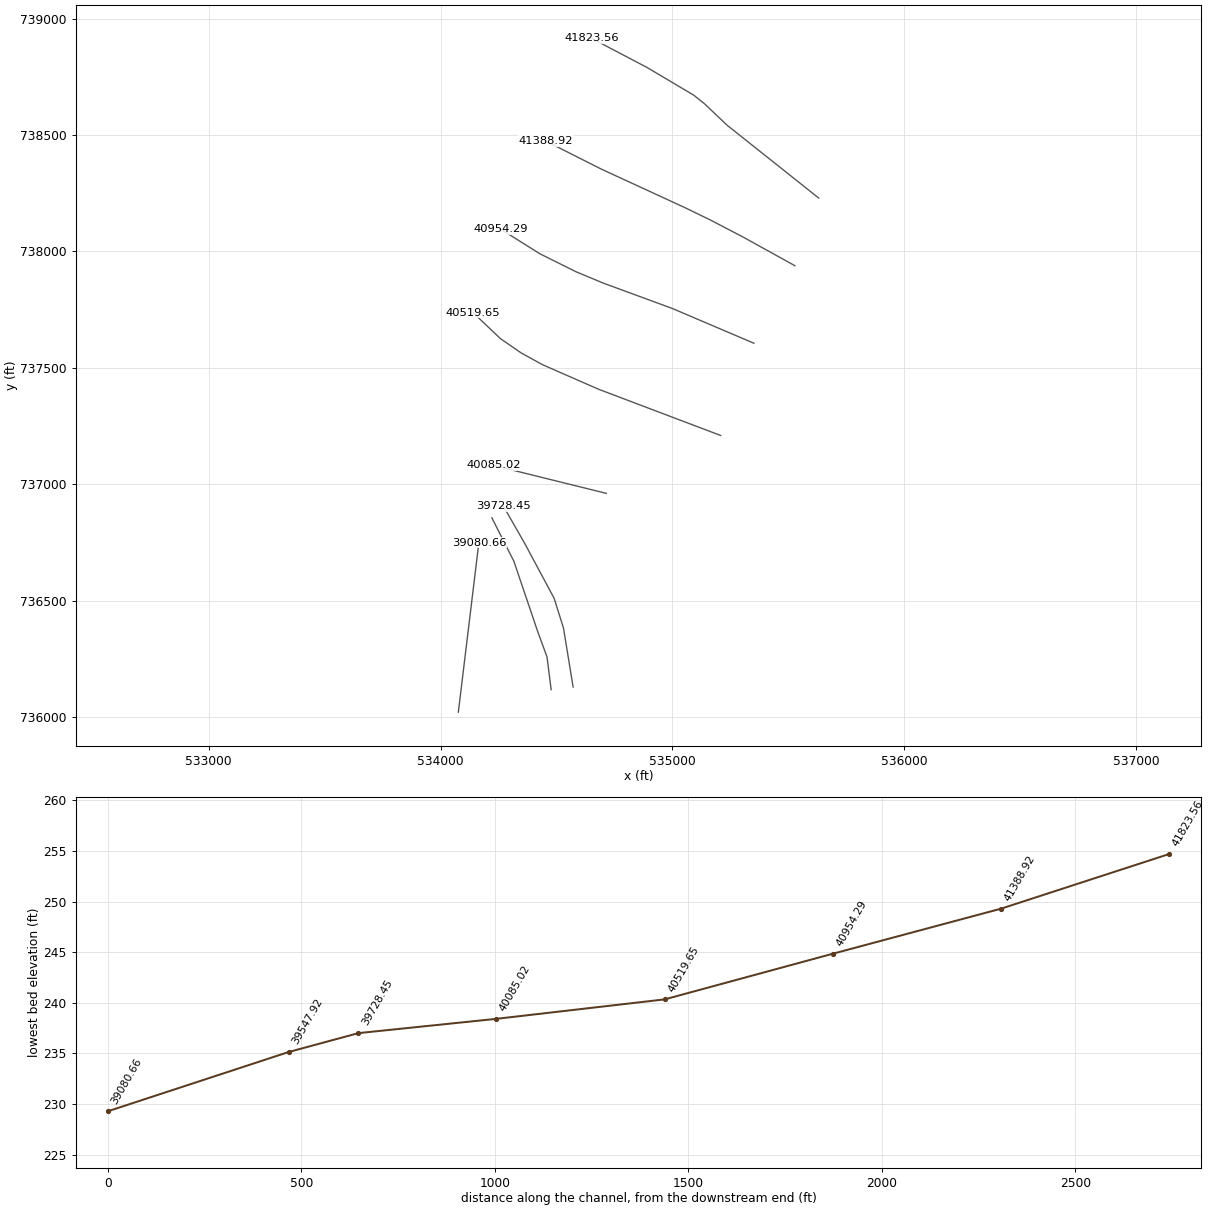
HEC-RAS study 1552_ras.prj: 1552

--- 1552_ras.g01 (geometry) --- (continued)

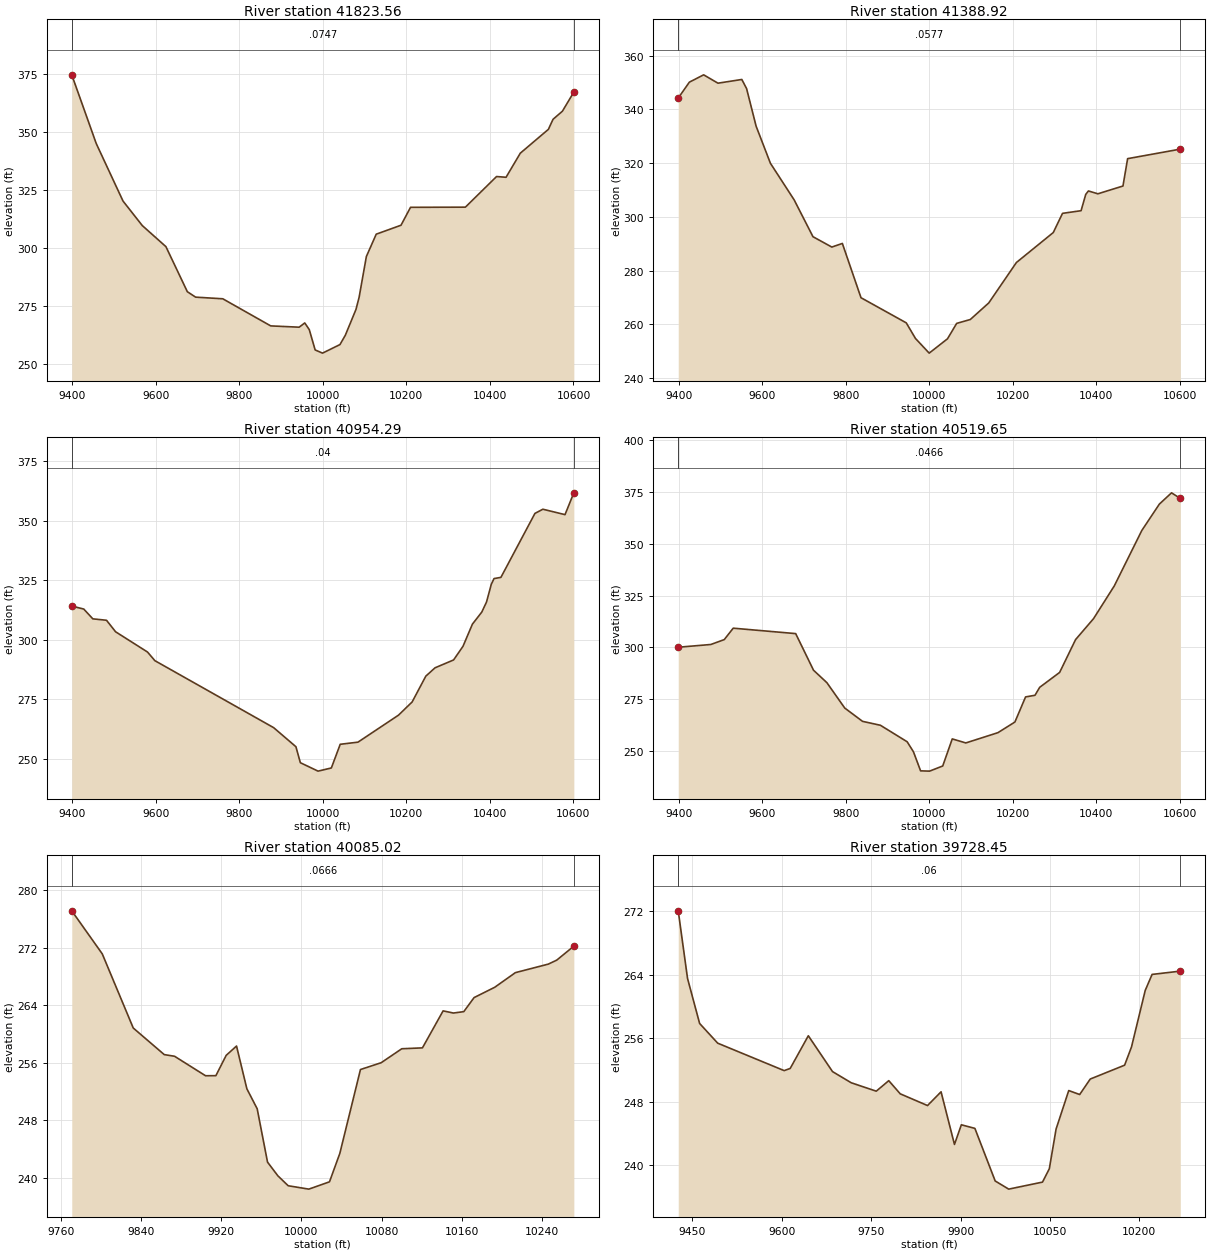
Type RM Length L Ch R = 1 ,41823.56,434.634900,434.634900,434.634900
XS GIS Cut Line= 6
535630.617239458738229.207287646535235.083428635738542.209820978
535137.533697677738634.520261608535091.550932917738670.974982677
534889.808870243738790.020745769534650.496471464738915.156144941
#Sta/Elev= 30
9399.034 374.6099457.571 345.0229521.732320.22429567.854 309.6589624.389300.5953
9675.718281.16669695.515278.82829760.553278.12129875.258266.4436 9943.36265.8846
9956.774267.71129967.559264.85329981.668256.07819999.307254.710510041.07258.3993
10053.83262.392310079.35273.5223 10086.9278.782310104.26296.338310127.89  305.96
10187.15309.808310209.97317.527110341.28317.595510415.89330.788510438.63330.4707
10472.74340.849710539.99351.118310551.17355.466610573.53358.929610600.91 367.169
#Mann= 3 , 0 , 0
9399.034  0.0747       09399.034  0.0747       010600.91  0.0747       0
#XS Ineff= 2 , 0
       0                               0
Bank Sta=9399.034,10600.91
Exp/Cntr=0.3,0.1

Type RM Length L Ch R = 1 ,41388.92,434.634800,434.634800,434.634800
XS GIS Cut Line= 6
535528.325147889737938.441485908535305.646631553738061.097669854
535161.699318514738135.824259307535049.754662538 738189.80912499
534694.202286641738352.902614498534452.827864655738474.083183022
#Sta/Elev= 30
9399.015344.24979425.644350.16539459.894352.90139494.144349.79139551.228 351.171
9562.644347.78939585.478333.77919619.728319.97119676.502306.36099721.571292.6498
 9766.64288.78729791.934290.13259836.551269.93019944.929260.57259966.884254.7802
9999.806249.304710043.67254.646410065.61260.379310098.19261.8137 10142.4267.9844
10208.57283.028610296.89294.195910318.97301.338110363.43302.323510374.57308.3828
   10381309.669610403.68308.614910463.71311.512710474.85321.694510600.99 325.242
#Mann= 3 , 0 , 0
9399.015  0.0577       09399.015  0.0577       010600.99  0.0577       0
#XS Ineff= 2 , 0
       0                               0
Bank Sta=9399.015,10600.99
Exp/Cntr=0.3,0.1

Type RM Length L Ch R = 1 ,40954.29,434.634900,434.634900,434.634900
XS GIS Cut Line= 6
535351.265011287737605.751108962534999.048640087737755.182313105
534703.315698748737863.341611799534583.417836167737912.930252805
534427.702078482737990.133067993534257.530095412738096.562309487
#Sta/Elev= 30
9399.013314.17539427.648312.93069449.452308.81459482.158  308.229503.963303.3813
9580.278294.88369597.974291.24929882.356 263.1069935.645255.10169946.238248.3863
9988.609244.851510020.43246.176710041.67256.125210084.14257.0162 10181.3268.3761
10213.77273.891510246.63284.7578 10268.7288.252210313.09291.554310335.61297.2887
10358.14306.586410380.66311.684210391.92315.893610403.26323.295710409.85325.7246
10426.38326.2439 10507.8353.101210526.84354.862910579.81352.585110600.95361.7484
#Mann= 3 , 0 , 0
9399.013    0.04       09399.013    0.04       010600.95    0.04       0
#XS Ineff= 2 , 0
       0                               0
Bank Sta=9399.013,10600.95
Exp/Cntr=0.3,0.1

Type RM Length L Ch R = 1 ,40519.65,434.634900,434.634900,434.634900
XS GIS Cut Line= 6
535207.745873451   737209.769898534680.821581856737408.456747771
534438.737267445737513.997216016534347.116993008 737564.35023935
 534257.23930752737626.265859432 534140.53235783737736.709965611
#Sta/Elev= 30
 9399.01300.11269477.015 301.4389509.183303.79399530.629309.30729680.185306.6885
9722.879289.0249  9754.9283.01189797.594270.78369840.289  264.359882.983 262.469
9947.024254.50579962.158249.64689979.201240.470210000.75240.336610032.22242.8227
10054.98255.878810087.52253.938710164.25258.883710204.99264.029710230.52276.1447
10253.07276.934910264.35280.783410312.09287.963510350.26303.809110393.24313.9069
10442.96329.723610508.91356.486410550.86369.185310579.93374.617410600.95371.9051
#Mann= 3 , 0 , 0
 9399.01  0.0466       0 9399.01  0.0466       010600.95  0.0466       0
#XS Ineff= 2 , 0
       0                               0
Bank Sta=9399.01,10600.95
Exp/Cntr=0.3,0.1

Type RM Length L Ch R = 1 ,40085.02,356.572800,356.572800,356.572800
XS GIS Cut Line= 2
534714.528583258736961.292356893534228.417472154737081.084023565
#Sta/Elev= 30
9770.993277.16069801.405271.16929832.303260.8458  9863.2257.14369873.499256.9113
9904.397254.19879914.696254.21079924.995257.04319935.294258.33499945.594 252.385
9955.893249.59979966.192 242.1759976.491240.2715 9986.79238.885210007.39238.4139
10027.99239.430510038.29243.384910058.88255.064410079.48256.011310100.08257.9569
10120.68258.080110141.28263.230610151.58262.930610161.88 263.12110172.18265.0807
10192.77266.518110213.37268.554910246.22269.742710254.57270.294510271.65272.2415
#Mann= 3 , 0 , 0
9770.993  0.0666       09770.993  0.0666       010271.65  0.0666       0
#XS Ineff= 2 , 0
       09797.248                       0
Bank Sta=9770.993,10271.65
Exp/Cntr=0.3,0.1

Type RM Length L Ch R = 1 ,39728.45,180.524300,180.524300,180.524300
XS GIS Cut Line= 5
534571.533138782736129.588690415534529.735249907736383.591245919
534489.544972152736510.592523664534364.151305497736743.696134701
534270.909861088736906.064856887
#Sta/Elev= 30
 9426.19272.04859441.809 263.5319462.078257.86349492.481255.37929603.961251.9247
9614.095252.20019644.499256.31569685.087251.80279716.553250.39319758.508249.3356
9779.486 250.6599798.737249.00319844.533247.52599867.243 249.2569889.738242.6274
9901.308245.10249924.018244.65149958.083238.02719980.793237.0009 10037.5237.8857
10048.92239.566910060.28244.567710081.51249.415110099.88248.914810117.61 250.864
10175.26252.6096 10186.8254.894910209.86262.022710221.39264.040110268.74 264.455
#Mann= 3 , 0 , 0
 9426.19    0.06       0 9426.19    0.06       010268.74    0.06       0
#XS Ineff= 2 , 0
       09827.769        10087.59       0
Bank Sta=9426.19,10268.74
Exp/Cntr=0.3,0.1

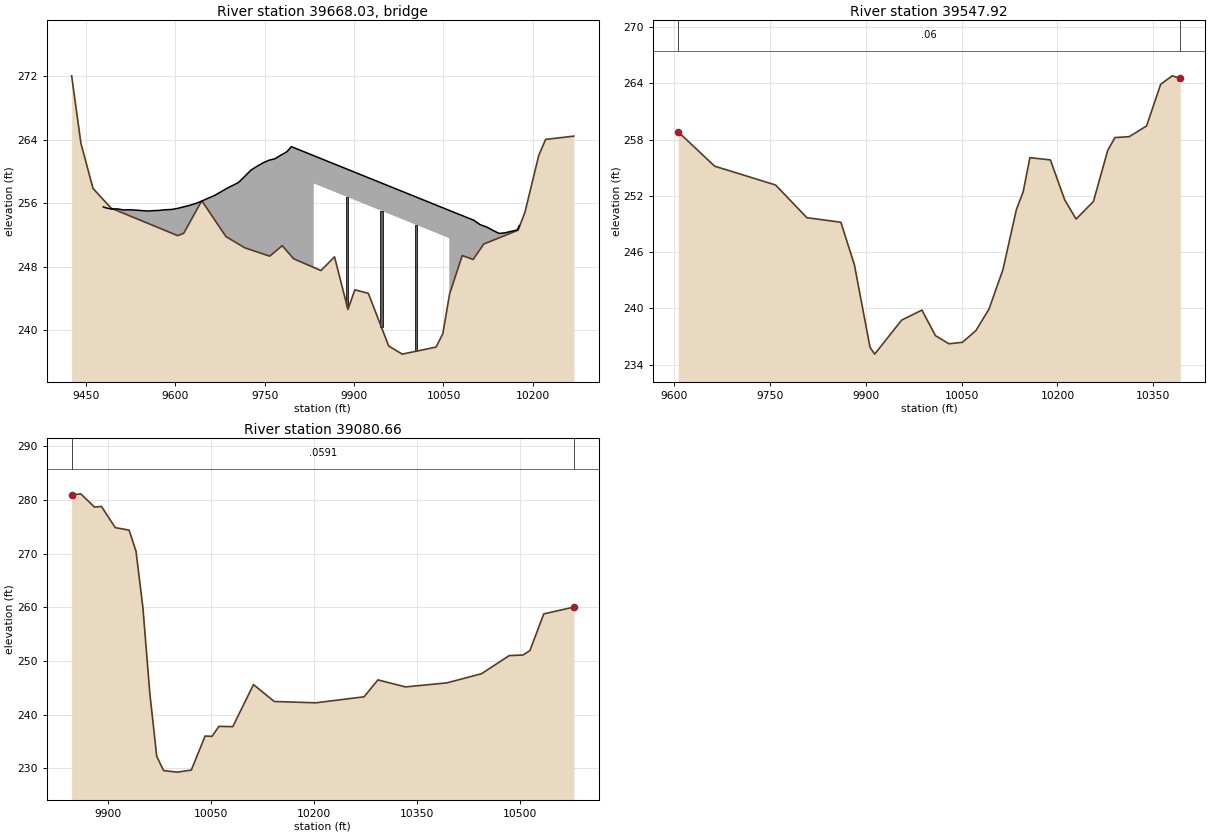
Type RM Length L Ch R = 3 ,39668.03,,,
BEGIN DESCRIPTION:
END DESCRIPTION:
Bridge Culvert--1,0,-1,-1, 0
Deck Dist Width WeirC Skew NumUp NumDn MinLoCord MaxHiCord MaxSubmerge Is_Ogee
72.381600,35.761100,2.6,0, 58, 58, , , 0.95, 0, 0,0,,
 9479.28 9483.07 9493.09 9499.50 9503.12 9513.14 9523.16 9533.18 9543.20 9553.23
 9563.25 9573.27 9580.45 9583.36 9593.60 9601.58 9603.85 9614.10 9624.35 9634.59
 9644.84 9647.35 9655.09 9665.34 9675.58 9685.83 9693.12 9696.08 9706.33 9716.58
 9726.82 9734.46 9737.02 9744.83 9747.06 9757.11 9767.15 9777.19 9787.24 9794.77
 9832.42 9832.4210059.7810059.7810099.2510099.4710099.9510111.2010121.2910122.45
10129.6110133.2810143.3810153.4810163.5910173.3710173.6910177.19
  255.54  255.43  255.27  255.29  255.29  255.16  255.18  255.14  255.08  255.02
  255.07  255.10  255.17  255.18  255.22  255.32  255.35  255.55  255.74  255.98
  256.28  256.37  256.64  256.96  257.39  257.85  258.13  258.23  258.63  259.39
  260.16  260.53  260.65  260.98  261.08  261.42  261.60  262.06  262.48  263.13
  261.99  261.99  255.10  255.10  253.91  253.92  253.91  253.32  253.04  253.01
  252.73  252.57  252.20  252.28  252.46  252.63  252.64  253.19
 -744.46 -744.57 -744.73 -744.71 -744.71 -744.84 -744.82 -744.86 -744.92 -744.98
 -744.93 -744.90 -744.83 -744.82 -744.78 -744.68 -744.65 -744.45 -744.26 -744.02
 -743.72 -743.63 -743.36 -743.04 -742.61 -742.15 -741.87 -741.77 -741.37 -740.61
 -739.84 -739.47 -739.35 -739.02 -738.92 -738.58 -738.40 -737.94 -737.52 -736.87
 -738.01  258.49  251.60 -744.90 -746.09 -746.08 -746.09 -746.68 -746.96 -746.99
 -747.27 -747.43 -747.80 -747.72 -747.54 -747.37 -747.36 -746.81
 9479.28 9483.07 9493.09 9499.50 9503.12 9513.14 9523.16 9533.18 9543.20 9553.23
 9563.25 9573.27 9580.45 9583.36 9593.60 9601.58 9603.85 9614.10 9624.35 9634.59
 9644.84 9647.35 9655.09 9665.34 9675.58 9685.83 9693.12 9696.08 9706.33 9716.58
 9726.82 9734.46 9737.02 9744.83 9747.06 9757.11 9767.15 9777.19 9787.24 9794.77
 9891.57 9891.5710099.2510099.4710099.9510111.2010118.9310118.9310121.2910122.45
10129.6110133.2810143.3810153.4810163.5910173.3710173.6910177.19
  255.54  255.43  255.27  255.29  255.29  255.16  255.18  255.14  255.08  255.02
  255.07  255.10  255.17  255.18  255.22  255.32  255.35  255.55  255.74  255.98
  256.28  256.37  256.64  256.96  257.39  257.85  258.13  258.23  258.63  259.39
  260.16  260.53  260.65  260.98  261.08  261.42  261.60  262.06  262.48  263.13
  260.20  260.20  253.91  253.92  253.91  253.32  253.11  253.11  253.04  253.01
  252.73  252.57  252.20  252.28  252.46  252.63  252.64  253.19
 -744.46 -744.57 -744.73 -744.71 -744.71 -744.84 -744.82 -744.86 -744.92 -744.98
 -744.93 -744.90 -744.83 -744.82 -744.78 -744.68 -744.65 -744.45 -744.26 -744.02
 -743.72 -743.63 -743.36 -743.04 -742.61 -742.15 -741.87 -741.77 -741.37 -740.61
 -739.84 -739.47 -739.35 -739.02 -738.92 -738.58 -738.40 -737.94 -737.52 -736.87
 -739.80  256.70  250.41  250.42  250.41  249.82  249.61 -746.89 -746.96 -746.99
 -747.27 -747.43 -747.80 -747.72 -747.54 -747.37 -747.36 -746.81
Pier Skew, UpSta & Num, DnSta & Num=  ,9888.26, 2 ,9947.41, 2 , 0 , 0 , 0 ,,
    4.00    4.00
 -739.70  260.30
    4.00    4.00
 -741.49  258.51
Pier Skew, UpSta & Num, DnSta & Num=  ,9946.10, 2 ,10005.25, 2 , 0 , 0 , 0 ,,
    4.00    4.00
 -741.45  258.55
    4.00    4.00
 -743.24  256.76
Pier Skew, UpSta & Num, DnSta & Num=  ,10003.94, 2 ,10063.09, 2 , 0 , 0 , 0 ,,
    4.00    4.00
 -743.21  256.79
    4.00    4.00
 -745.00  255.00
BR Coef=-1 , 0 , 0 ,, 0 ,,,0.8,0,1,0,
WSPro=,,,, 1 ,,,, 0 ,,,, 0 ,,,,-1 ,-1 ,-1 , 0 , 0 , 0 , 0 , 0
BC Design=,, 0 ,, 0 ,,,,,,

Type RM Length L Ch R = 1 ,39547.92,467.262800,467.262800,467.262800
XS GIS Cut Line= 5
534476.684083253736118.335412636534459.000361055736258.197579265
 534417.20247215736372.337968156534315.922972172 736669.74602361
534221.073916644736856.228912443
#Sta/Elev= 30
 9606.38258.83639663.496255.16859758.989253.15849807.847249.67799861.094249.1877
9882.284244.65189906.762235.84699913.976235.13029956.232238.75719987.924239.8232
10009.05237.105210030.18236.234310051.31236.387710072.44237.640610092.89239.9316
10114.69244.128210135.82 250.55110146.38252.426410156.95256.076310188.98255.8329
10211.42251.574510229.24249.5333 10256.3251.396710278.74256.846310289.96258.2145
10312.39258.312510339.53259.459810361.59263.896710379.71264.798110392.31264.5348
#Mann= 3 , 0 , 0
 9606.38    0.06       0 9606.38    0.06       010392.31    0.06       0
#XS Ineff= 2 , 0
       09860.462        10175.26       0
Bank Sta=9606.38,10392.31
Exp/Cntr=0.3,0.1

Type RM Length L Ch R = 1 ,39080.66,648.508100,648.508100,648.508100
XS GIS Cut Line= 2
534076.388916701736021.878746018534164.807527781736748.518968061
#Sta/Elev= 30
9846.429280.89869859.647281.13119879.794 278.6599889.868278.78539910.016274.8274
9930.163274.37139940.237270.44059950.311259.90069960.385243.94069970.458232.2057
9980.532229.554810000.68229.271210020.83229.656110040.97235.996510051.05235.9372
10061.12237.803710081.27 237.74310111.49245.586110141.71242.433610202.15242.1886
10272.67243.306610292.82246.458910333.11245.152510393.56245.905310443.93247.6142
10484.22250.984210504.37251.095910514.44251.928710534.59 258.75710578.43260.0233
#Mann= 3 , 0 , 0
9846.429  0.0591       09846.429  0.0591       010578.43  0.0591       0
#XS Ineff= 2 , 0
       0                               0
Bank Sta=9846.429,10578.43
Exp/Cntr=0.3,0.1