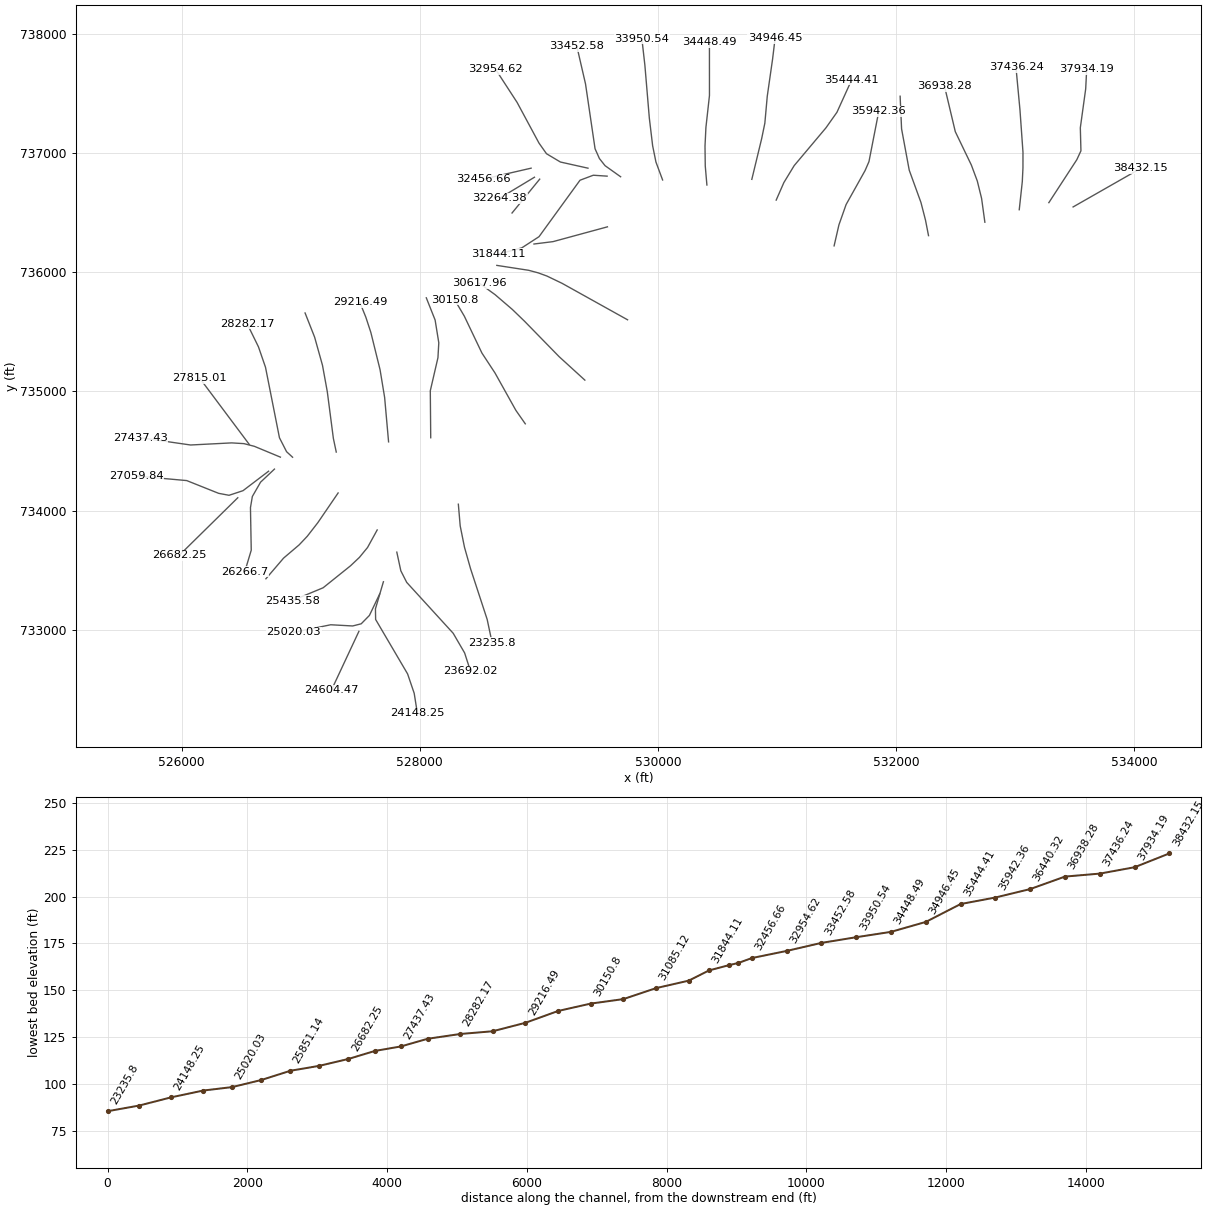
HEC-RAS study 1552_ras.prj: 1552

--- 1552_ras.g01 (geometry) --- (continued)

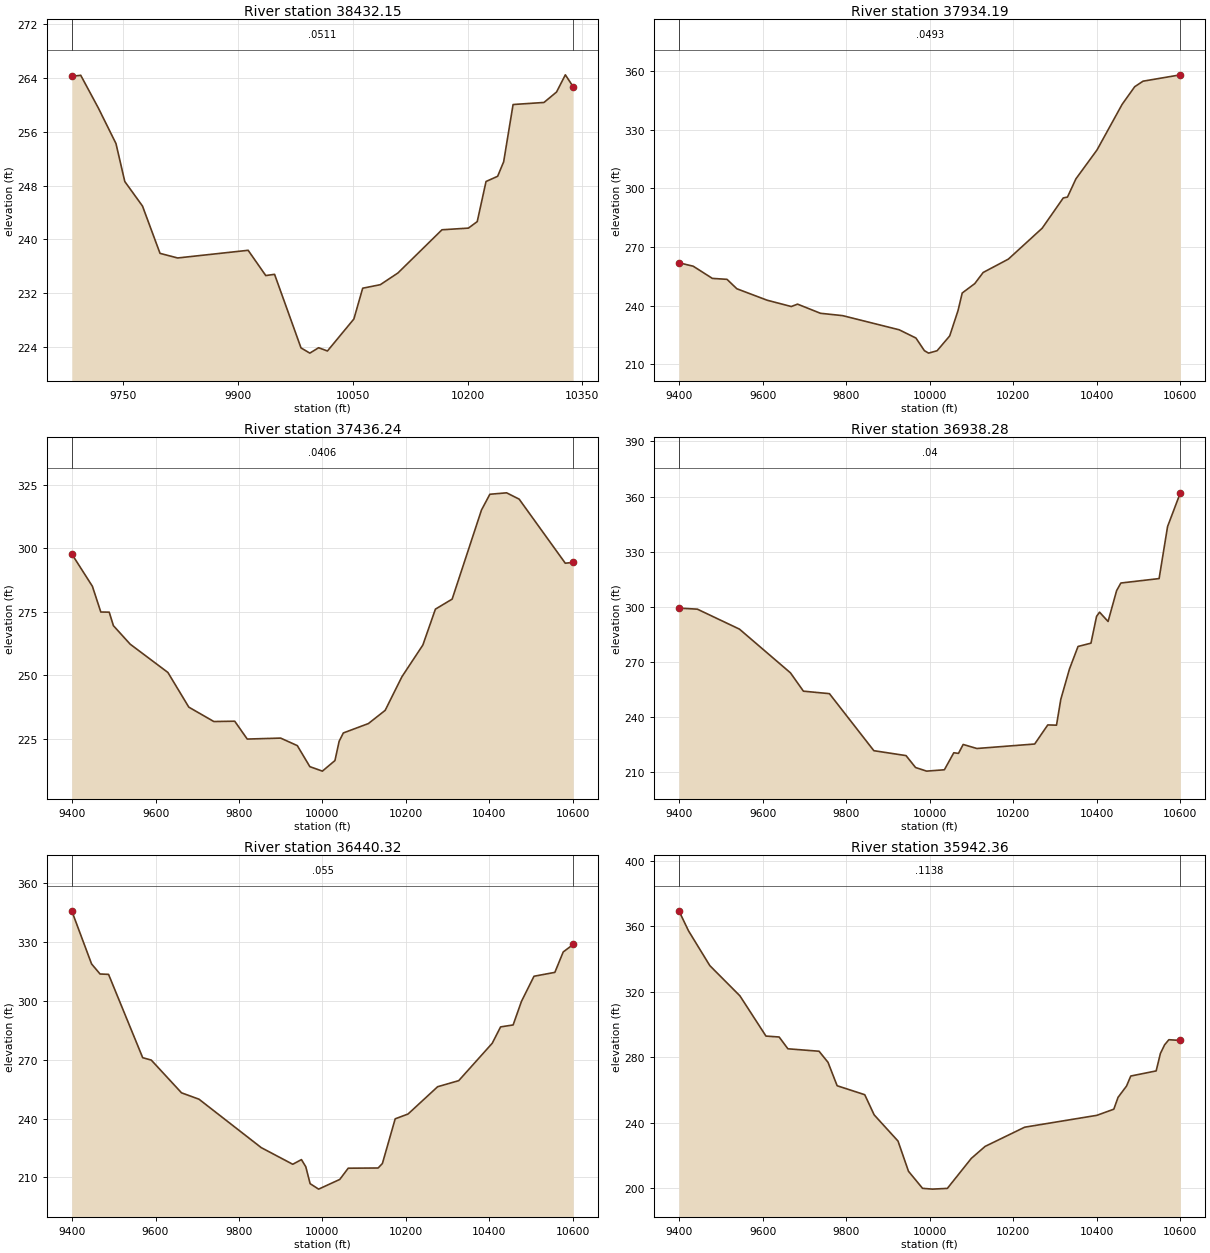
Type RM Length L Ch R = 1 ,38432.15,497.957200,497.957200,497.957200
XS GIS Cut Line= 2
533484.788028002  736549.1751903534053.882361174736873.912634686
#Sta/Elev= 30
 9682.68264.25969694.437264.42489717.464259.54889740.491254.25929752.005 248.608
9775.141244.95389798.059237.91019821.086237.22429913.194238.36639936.221234.6071
9947.734 234.7879982.275223.83719993.788223.0565 10005.3223.861610016.82223.3745
10051.36 228.13710062.87232.7213 10085.9233.246510108.92 234.98910166.49 241.422
10201.03241.669910212.55242.638610224.06248.610910239.22 249.38610247.09251.5456
10259.39260.070110299.75260.378410316.17261.928310327.68 264.49210337.91262.7255
#Mann= 3 , 0 , 0
 9682.68  0.0511       0 9682.68  0.0511       010337.91  0.0511       0
#XS Ineff= 2 , 0
       0                               0
Bank Sta=9682.68,10337.91
Exp/Cntr=0.3,0.1

Type RM Length L Ch R = 1 ,37934.19,497.957200,497.957200,497.957200
XS GIS Cut Line= 6
533281.182220562736585.236038322533516.019447489736945.907277012
533550.604152466737020.418989317533545.463603787737214.247832532
533590.523748305737540.367144867533598.919568004737704.293011919
#Sta/Elev= 30
9399.162261.86069433.386260.1173 9479.38253.86889514.416253.39849538.067248.5727
 9610.36242.73989668.461239.49879683.495240.70979738.417236.0404 9791.56234.8351
9927.066227.60669967.268223.38559987.472216.94389997.653215.669310018.02216.9035
10048.17 224.47910068.18237.462710078.19246.414610108.22251.212810128.34256.8986
10188.82263.744410269.76279.523410320.34294.997910330.46295.4707 10350.7304.7814
10401.11319.516410461.44342.865110491.53351.873910511.58 354.70610600.94357.9552
#Mann= 3 , 0 , 0
9399.162  0.0493       09399.162  0.0493       010600.94  0.0493       0
#XS Ineff= 2 , 0
       0                               0
Bank Sta=9399.162,10600.94
Exp/Cntr=0.3,0.1

Type RM Length L Ch R = 1 ,37436.24,497.957200,497.957200,497.957200
XS GIS Cut Line= 6
533032.655193372736525.874018198 533058.27072512736761.552660091
533063.804254212736876.441192115533064.004040377737008.656439122
533038.627679843737365.000477098533004.924886211737723.751864097
#Sta/Elev= 30
9399.041297.71899448.558284.96969468.717 274.8499488.876274.79119498.956269.4679
9539.191262.18839629.564251.07049679.642237.43139739.711 231.7649789.724231.8961
9819.724 224.8729899.743225.24899939.788222.28919969.823214.01699999.907212.2575
   10030216.425610040.03224.001410050.06227.273410110.25230.976710150.38236.1672
 10190.5249.385510240.66261.846510270.77275.970910310.93279.9248 10381.2314.9622
10401.28321.168710441.45321.7328 10471.6319.241510582.15294.0414   10601294.3808
#Mann= 3 , 0 , 0
9399.041  0.0406       09399.041  0.0406       0   10601  0.0406       0
#XS Ineff= 2 , 0
       0                               0
Bank Sta=9399.041,10601
Exp/Cntr=0.3,0.1

Type RM Length L Ch R = 1 ,36938.28,497.957100,497.957100,497.957100
XS GIS Cut Line= 6
532744.057836742736421.064603429532716.640672433736620.253704322
532680.547080401736766.796727365 532630.79848415736900.485614987
532495.785981534737181.073321059532404.601034218737565.099266243
#Sta/Elev= 30
9399.075299.35799443.304298.78259544.167287.9263 9666.46 264.1379697.512254.1706
9759.845252.82279866.327221.79659943.449219.13059966.233212.65589992.844210.6825
 10035.4211.420510057.93220.672110069.19220.342210080.43225.188310113.25222.9925
10251.81 225.43210283.22235.816810304.12 235.67710314.44249.757910335.08266.1455
10355.72278.488910386.69280.287810400.13294.847810407.27297.146510427.73292.0856
10448.19308.863810458.42313.003310550.04315.420210570.36343.734710600.95362.0636
#Mann= 3 , 0 , 0
9399.075    0.04       09399.075    0.04       010600.95    0.04       0
#XS Ineff= 2 , 0
       0                               0
Bank Sta=9399.075,10600.95
Exp/Cntr=0.3,0.1

Type RM Length L Ch R = 1 ,36440.32,497.957200,497.957200,497.957200
XS GIS Cut Line= 6
532270.932617065 736308.36692768532245.704011792736438.051606428
532207.557258387736586.345403989532108.950217017736858.233428986
 532044.75280273 737204.76014824532032.555853311737478.866751011
#Sta/Elev= 30
9399.108345.96799446.616 318.8879466.991313.74699487.366313.55229569.185271.0523
9589.734269.83129662.234253.12719704.049249.88019853.269225.17949928.848216.6805
9949.662 219.0589960.068215.43059970.475206.78569990.833204.0015 10041.5208.9422
10061.79214.677210133.44214.776710143.68217.069610174.38239.868910205.09242.3079
 10276.1256.239310326.66259.338310406.93278.402810426.99286.756910457.03287.7517
10477.04299.801510507.06 312.59410557.07314.575810577.07324.990210600.94328.7979
#Mann= 3 , 0 , 0
9399.108   0.055       09399.108   0.055       010600.94   0.055       0
#XS Ineff= 2 , 0
       0                               0
Bank Sta=9399.108,10600.94
Exp/Cntr=0.3,0.1

Type RM Length L Ch R = 1 ,35942.36,497.957200,497.957200,497.957200
XS GIS Cut Line= 6
531478.283874804736222.331401088531518.817207469736398.840675242
531578.874990295736569.101005692531738.105509042736854.187632564
531770.968706593736929.661879901531853.427661077737352.087010871
#Sta/Elev= 30
9399.064369.53599422.185357.26949473.185336.0484 9545.27317.59779607.744293.0003
9639.288292.44659660.317 285.2389734.978283.74099756.454276.96869778.319262.6621
9844.502257.18639867.044 244.8719924.235228.86069949.325210.40849983.024199.9836
10006.71199.493910042.52199.9498 10099.9218.2719 10133.1225.614710227.81237.3348
10400.89244.5854 10441.5248.341110451.65255.577310471.95262.4757 10482.1268.5929
   10543271.727910553.15282.3933 10563.3287.692110573.45290.786910600.94290.3383
#Mann= 3 , 0 , 0
9399.064  0.1138       09399.064  0.1138       010600.94  0.1138       0
#XS Ineff= 2 , 0
       0                               0
Bank Sta=9399.064,10600.94
Exp/Cntr=0.3,0.1

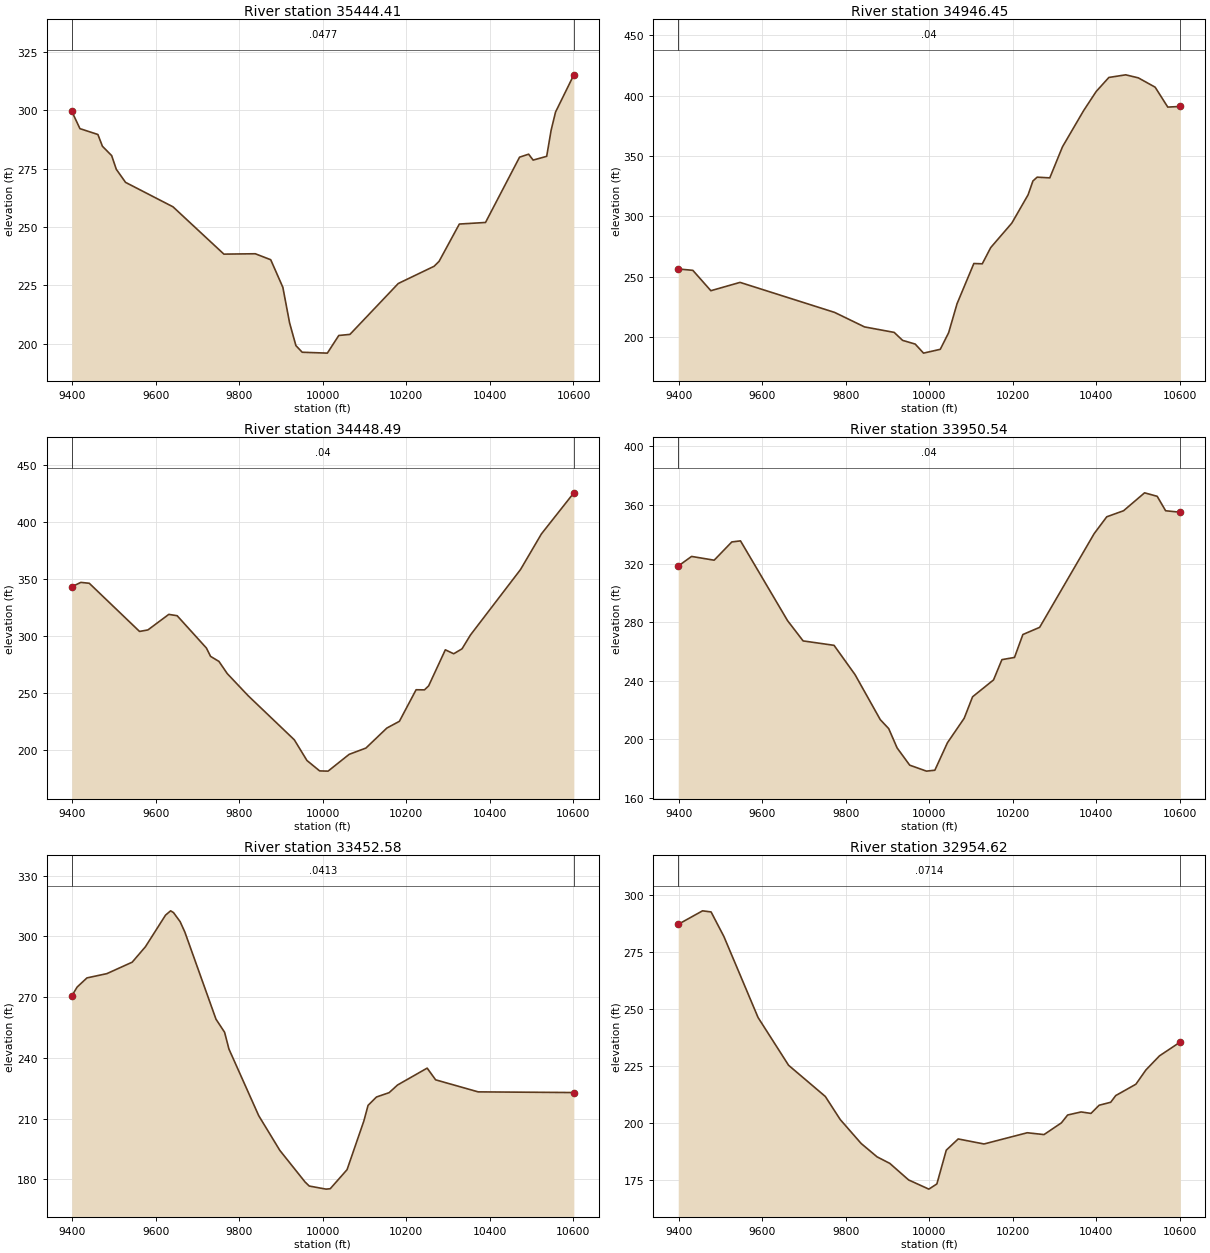
Type RM Length L Ch R = 1 ,35444.41,497.957200,497.957200,497.957200
XS GIS Cut Line= 6
530992.114022422736606.783405418531056.615223562736754.064592505
531143.076042492 736896.15988622531409.749822437737213.219583075
531502.013742554737343.780536464531625.906947934737616.351954976
#Sta/Elev= 30
9399.076299.6481 9418.64292.2017  9461.6   289.79472.478284.64859494.606280.6349
 9505.67274.77969527.798269.18069641.463258.69629763.241 238.4299838.348238.5875
9875.324236.02659904.361 224.2169920.545208.92279935.618199.23589950.692196.3833
10010.88196.005810038.24203.567910064.98204.032410180.65225.8429 10266.4233.2223
10278.37235.341510326.82251.3187 10389.5251.996610470.98279.974110492.67281.2619
10503.51278.725110535.95280.339710546.54291.526310557.13299.306910600.93315.2621
#Mann= 3 , 0 , 0
9399.076  0.0477       09399.076  0.0477       010600.93  0.0477       0
#XS Ineff= 2 , 0
       0                               0
Bank Sta=9399.076,10600.93
Exp/Cntr=0.3,0.1

Type RM Length L Ch R = 1 ,34946.45,497.957200,497.957200,497.957200
XS GIS Cut Line= 6
530787.482309671736780.916051388 530870.22678752737123.182174003
530896.842229106737252.679511508 530917.14927968 737479.03458022
530961.977503863737791.851090832 530982.85701189737964.796408586
#Sta/Elev= 30
9399.033256.27839434.008255.12229477.133238.23369547.005245.13449773.351220.2381
9845.081208.19259915.983203.65119936.149197.02869966.262193.97429986.299186.4475
10026.36189.6191 10046.4203.4082 10066.5227.426310106.71260.799410126.89260.5431
10147.09 273.99710197.61294.3134 10236.6 317.80310248.12329.248210258.22332.4175
10288.52331.841710318.83357.574110369.34387.541610399.65403.541110429.95415.1451
10470.24 417.32710500.45 414.81810540.74407.075110570.96390.560710600.98391.0806
#Mann= 3 , 0 , 0
9399.033    0.04       09399.033    0.04       010600.98    0.04       0
#XS Ineff= 2 , 0
       0                               0
Bank Sta=9399.033,10600.98
Exp/Cntr=0.3,0.1

Type RM Length L Ch R = 1 ,34448.49,497.957200,497.957200,497.957200
XS GIS Cut Line= 6
530410.307268577736733.375264324 530396.55181524736893.643227829
 530394.41893106 737060.05436764530402.111864705737216.851228418
530431.841869222737484.709876519530431.595944318737932.599988413
#Sta/Elev= 30
9399.032343.11229420.791346.92669440.915346.15759561.285303.83059581.294305.1682
9631.317318.83389651.319317.64859721.319289.27429731.322281.93659751.333277.5219
9771.344266.76919821.388247.34389931.813208.63819962.055190.47239992.396181.3336
10012.61 181.13510063.08 195.87410103.18201.387310153.31 218.97510183.32224.8911
10223.34252.620610243.34252.511910253.34256.034410293.34287.685310313.34284.2243
10333.34288.587310353.34300.664510473.35358.237410523.36389.534810600.96425.6028
#Mann= 3 , 0 , 0
9399.032    0.04       09399.032    0.04       010600.96    0.04       0
#XS Ineff= 2 , 0
       0                               0
Bank Sta=9399.032,10600.96
Exp/Cntr=0.3,0.1

Type RM Length L Ch R = 1 ,33950.54,497.957100,497.957100,497.957100
XS GIS Cut Line= 6
530038.403853694736775.743319411529982.469558852736926.338370269
529954.825190294737062.685348917529926.968859738737295.644395467
529889.747626924737737.761257971529864.593415636737959.901783434
#Sta/Elev= 30
 9399.05318.29819431.002324.8556 9485.08322.2781 9527.28334.74249548.118335.4775
9660.865 280.9719698.072 267.1719772.055264.15259822.419244.11029882.784213.3974
9902.905207.30849923.027194.12349953.156182.35419993.289178.276710013.36178.8883
10043.46197.621910083.61214.369110103.68229.024710153.86240.548410173.93254.3938
10204.04255.894110224.11271.540610264.25276.445210394.75 340.421 10424.9351.9124
10465.11 356.04310515.45368.275710545.67365.897610565.82356.037210600.99355.0201
#Mann= 3 , 0 , 0
 9399.05    0.04       0 9399.05    0.04       010600.99    0.04       0
#XS Ineff= 2 , 0
       0                               0
Bank Sta=9399.05,10600.99
Exp/Cntr=0.3,0.1

Type RM Length L Ch R = 1 ,33452.58,497.957200,497.957200,497.957200
XS GIS Cut Line= 6
529685.936868264736802.614428028529555.217412552736895.762699778
529508.039554927736955.425199156529471.348348294737037.673036863
   529391.302596737581.868548469529318.527229178737897.378597013
#Sta/Elev= 30
 9399.08270.62419411.918275.00629435.394279.51689483.058 281.6259543.689 287.279
9575.341294.88359623.518310.49729635.671312.63799642.577311.77519658.442307.3118
9669.777 302.161  9744.3259.14919764.963252.66779775.294244.41739846.672211.4839
9897.148 194.3799957.528178.76649967.577176.761510007.78175.240910017.84175.4437
10058.07184.8498 10098.3208.886110108.35216.5928 10128.5220.721510158.78222.8685
10178.97226.652510249.84234.982110270.11229.200510371.99223.255910600.97222.9232
#Mann= 3 , 0 , 0
 9399.08  0.0413       0 9399.08  0.0413       010600.97  0.0413       0
#XS Ineff= 2 , 0
       0                10184.74       0
Bank Sta=9399.08,10600.97
Exp/Cntr=0.3,0.1

Type RM Length L Ch R = 1 ,32954.62,497.957200,497.957200,497.957200
XS GIS Cut Line= 6
  529411.8908284736874.699449093529180.530801326736926.347542516
529063.733914485736995.950694712529000.595944481737085.329646148
528816.928624049737426.674587138528637.189138117737703.247641077
#Sta/Elev= 30
9399.055287.01549457.248292.93169477.705 292.4429508.391281.66199590.221246.1514
9663.239225.2319 9751.18211.55479786.875 201.4369836.953190.94669875.005185.0974
9905.546182.22129950.613174.9644    9999170.941710018.21173.223210040.74188.0165
10069.26192.939210131.02190.733110234.62195.653710274.71194.8502 10316.3199.9902
10331.24203.431210363.49204.774610387.09204.133210406.62207.712210434.37209.0215
10446.42211.958110494.62216.926410518.72223.205310551.13229.362610600.97 235.438
#Mann= 3 , 0 , 0
9399.055  0.0714       09399.055  0.0714       010600.97  0.0714       0
#XS Ineff= 2 , 0
       0                10069.63       0
Bank Sta=9399.055,10600.97
Exp/Cntr=0.3,0.1

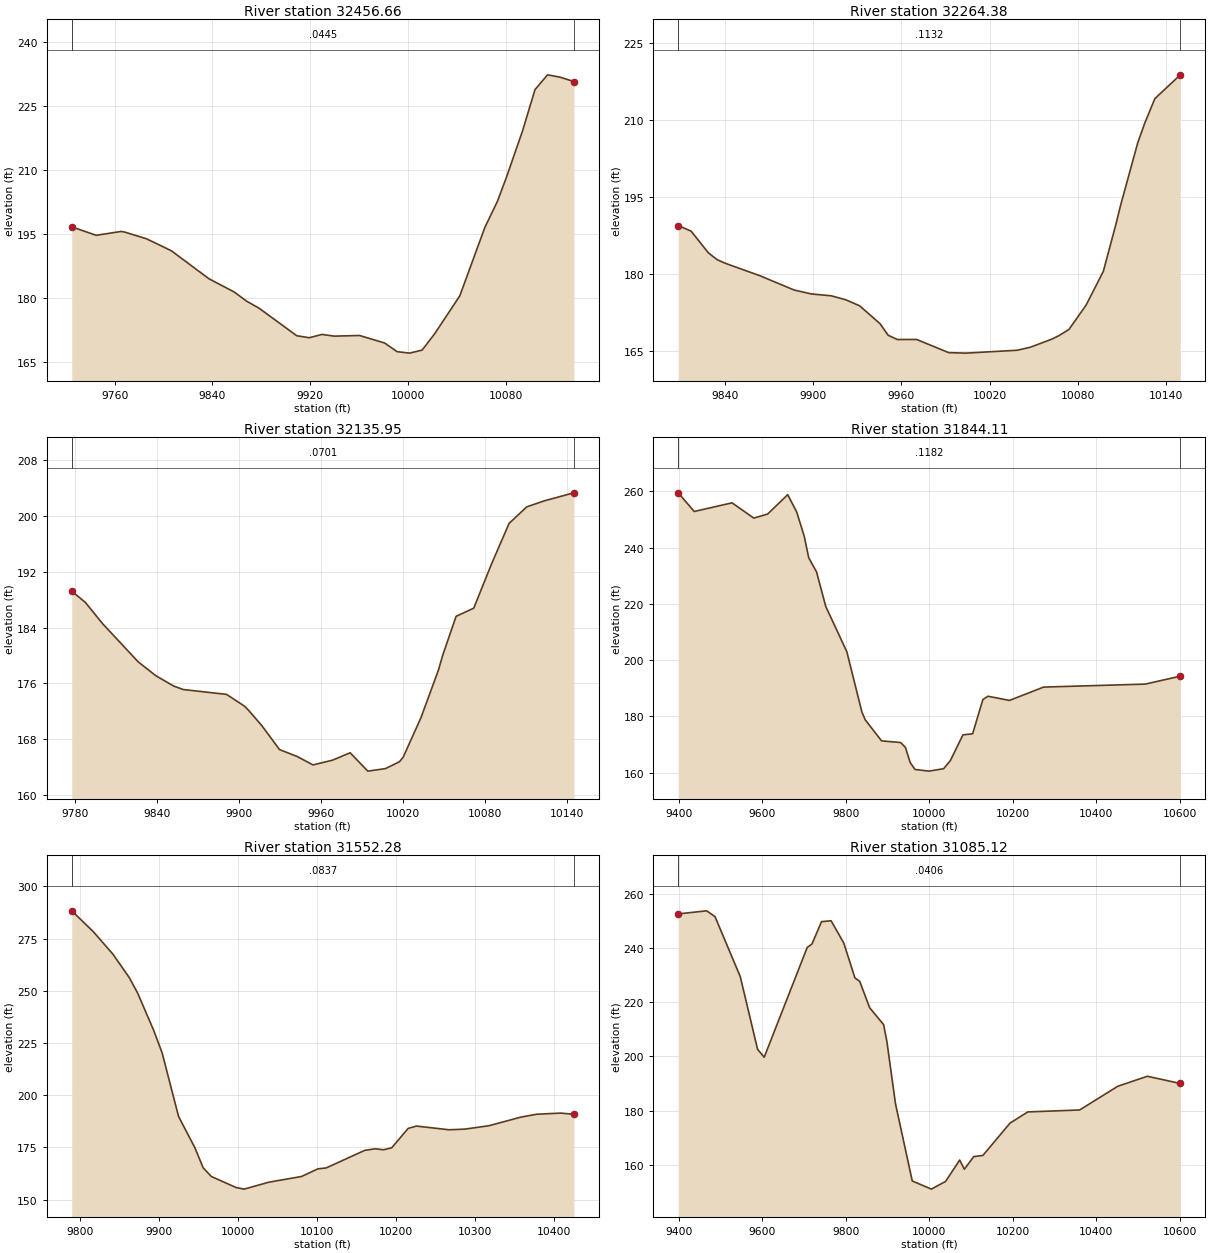
Type RM Length L Ch R = 1 ,32456.66,192.283500,192.283500,192.283500
XS GIS Cut Line= 2
528934.488098085736874.750132665 528534.02928251 736782.64460507
#Sta/Elev= 30
9724.828196.67099744.825194.69149765.347195.59939768.327195.4336 9785.87193.8867
9796.131192.49259806.392191.06229837.175184.51699857.697181.44719867.958179.2874
9878.219177.62199909.003171.20149919.264170.73889929.525171.50889939.786171.1119
9960.308171.2629 9980.83169.51369991.091167.483310001.35167.138210011.61167.8526
10021.87171.6812 10042.4 180.52910062.92196.537310073.18202.623610080.62208.3016
 10093.7219.060910103.96228.768910114.22232.222210124.49231.669910135.74230.6593
#Mann= 3 , 0 , 0
9724.828  0.0445       09724.828  0.0445       010135.74  0.0445       0
#XS Ineff= 2 , 0
       0                               0
Bank Sta=9724.828,10135.74
Exp/Cntr=0.3,0.1

Type RM Length L Ch R = 1 ,32264.38,128.428700,128.428700,128.428700
XS GIS Cut Line= 2
528962.520215183736798.662957713528670.185279816736622.461078838
#Sta/Elev= 30
 9808.24189.43379817.021188.34059828.697184.11729834.707  182.779840.373182.0522
9863.725179.64319887.077176.84139898.753 176.0839912.194175.72389922.105174.9461
9931.565173.76649945.457170.26969950.937168.01999957.133167.18569970.309167.1925
9992.161164.616310003.84164.525210038.87165.091810047.79165.692910062.22167.2554
10067.17167.954610073.89169.155710085.57173.928310097.25180.497210105.91189.8171
10108.92193.3328 10120.6205.554510125.28209.348410132.27214.215410149.57218.8655
#Mann= 3 , 0 , 0
 9808.24  0.1132       0 9808.24  0.1132       010149.57  0.1132       0
#XS Ineff= 2 , 0
       0                               0
Bank Sta=9808.24,10149.57
Exp/Cntr=0.3,0.1

Type RM Length L Ch R = 1 ,32135.95,291.837900,291.837900,291.837900
XS GIS Cut Line= 2
 529006.57068491 736782.64460507528774.304571867736498.318846002
#Sta/Elev= 30
9777.846189.21239787.717187.6221 9800.63184.50779826.455179.07589839.367 177.089
 9852.28175.62019859.362175.11069891.017174.4165 9903.93 172.7579906.782172.2123
9916.842169.93339929.755166.50269942.667165.50889954.202 164.3039968.492164.9784
9981.405166.04439994.317163.409110007.23163.769910017.43164.749410020.14165.3879
10033.24171.097310045.97177.899610049.04179.997410058.88185.608810071.79186.7841
 10084.7193.078910097.62198.938510110.53201.311910123.44202.180910144.98203.3262
#Mann= 3 , 0 , 0
9777.846  0.0701       09777.846  0.0701       010144.98  0.0701       0
#XS Ineff= 2 , 0
       0                               0
Bank Sta=9777.846,10144.98
Exp/Cntr=0.3,0.1

Type RM Length L Ch R = 1 ,31844.11,291.837900,291.837900,291.837900
XS GIS Cut Line= 6
529572.726457005736807.758515042529456.506355879736815.450989455
529344.993318051736773.526139245529001.059046565736299.789699451
528856.028315321736205.508518485528662.667867009 736153.89629928
#Sta/Elev= 30
 9399.04259.49419437.319252.86119527.801255.93349579.905250.5084 9613.07251.9452
9661.039258.83349682.506252.73339700.728244.01169711.348236.41519730.104231.3782
9752.226219.0713 9802.58203.00569838.773181.50219846.741 178.7669885.802171.2844
9931.497170.70179942.921168.96029954.345163.55959965.769161.1324    9999160.5303
10034.25161.388810050.46 164.27910080.49173.416710103.77173.816610128.27185.9891
10140.58187.161410191.92 185.675 10273.7190.415410517.12191.477510600.85194.2981
#Mann= 3 , 0 , 0
 9399.04  0.1182       0 9399.04  0.1182       010600.85  0.1182       0
#XS Ineff= 2 , 0
       0                               0
Bank Sta=9399.04,10600.85
Exp/Cntr=0.3,0.1

Type RM Length L Ch R = 1 ,31552.28,467.158100,467.158100,467.158100
XS GIS Cut Line= 3
529575.222203046736382.185789496529118.699153304 736258.04355666
528958.515627027736238.020615891
#Sta/Elev= 30
9790.042288.25939817.427278.21629842.088267.50429862.814256.24299873.178248.9797
9893.646230.98169904.267220.24749924.993 189.863 9945.72174.81369956.083165.2599
9966.446161.10669997.535155.8498 10007.9155.054910038.99 158.36510080.44161.1057
10101.17164.755810111.53 165.19410160.41173.626810173.71174.359810184.07173.8836
10194.43174.834210215.16184.110310225.52185.242410266.87183.459210287.03183.7854
10317.26185.394610357.57189.522410377.73190.905210407.96191.447310424.57 190.896
#Mann= 3 , 0 , 0
9790.042  0.0837       09790.042  0.0837       010424.57  0.0837       0
#XS Ineff= 2 , 0
       0                               0
Bank Sta=9790.042,10424.57
Exp/Cntr=0.3,0.1

Type RM Length L Ch R = 1 ,31085.12,467.158100,467.158100,467.158100
XS GIS Cut Line= 6
529744.356249612735601.719048785529194.216118364735908.043203668
529066.649515566735969.365173833528992.824395797735996.184995181
 528913.60460163736017.425361228528646.734034839736058.544188239
#Sta/Elev= 30
9399.002252.53169467.153253.65589487.087251.50369547.524229.39039588.965 202.603
9604.827199.6926 9707.72 240.1449719.152241.42159742.017249.65579764.883250.0051
9795.289241.78789822.045228.90119833.478227.64939857.186217.93639890.641211.7239
9898.451205.55139919.084182.54189959.236154.080910004.96151.069510039.03153.9157
10072.73161.787710083.96158.406810106.42 163.065 10128.3163.481610193.31175.4057
10235.86179.5338 10359.9180.242410451.27188.987310521.92 192.67510600.91190.0091
#Mann= 3 , 0 , 0
9399.002  0.0406       09399.002  0.0406       010600.91  0.0406       0
#XS Ineff= 2 , 0
       0                               0
Bank Sta=9399.002,10600.91
Exp/Cntr=0.3,0.1

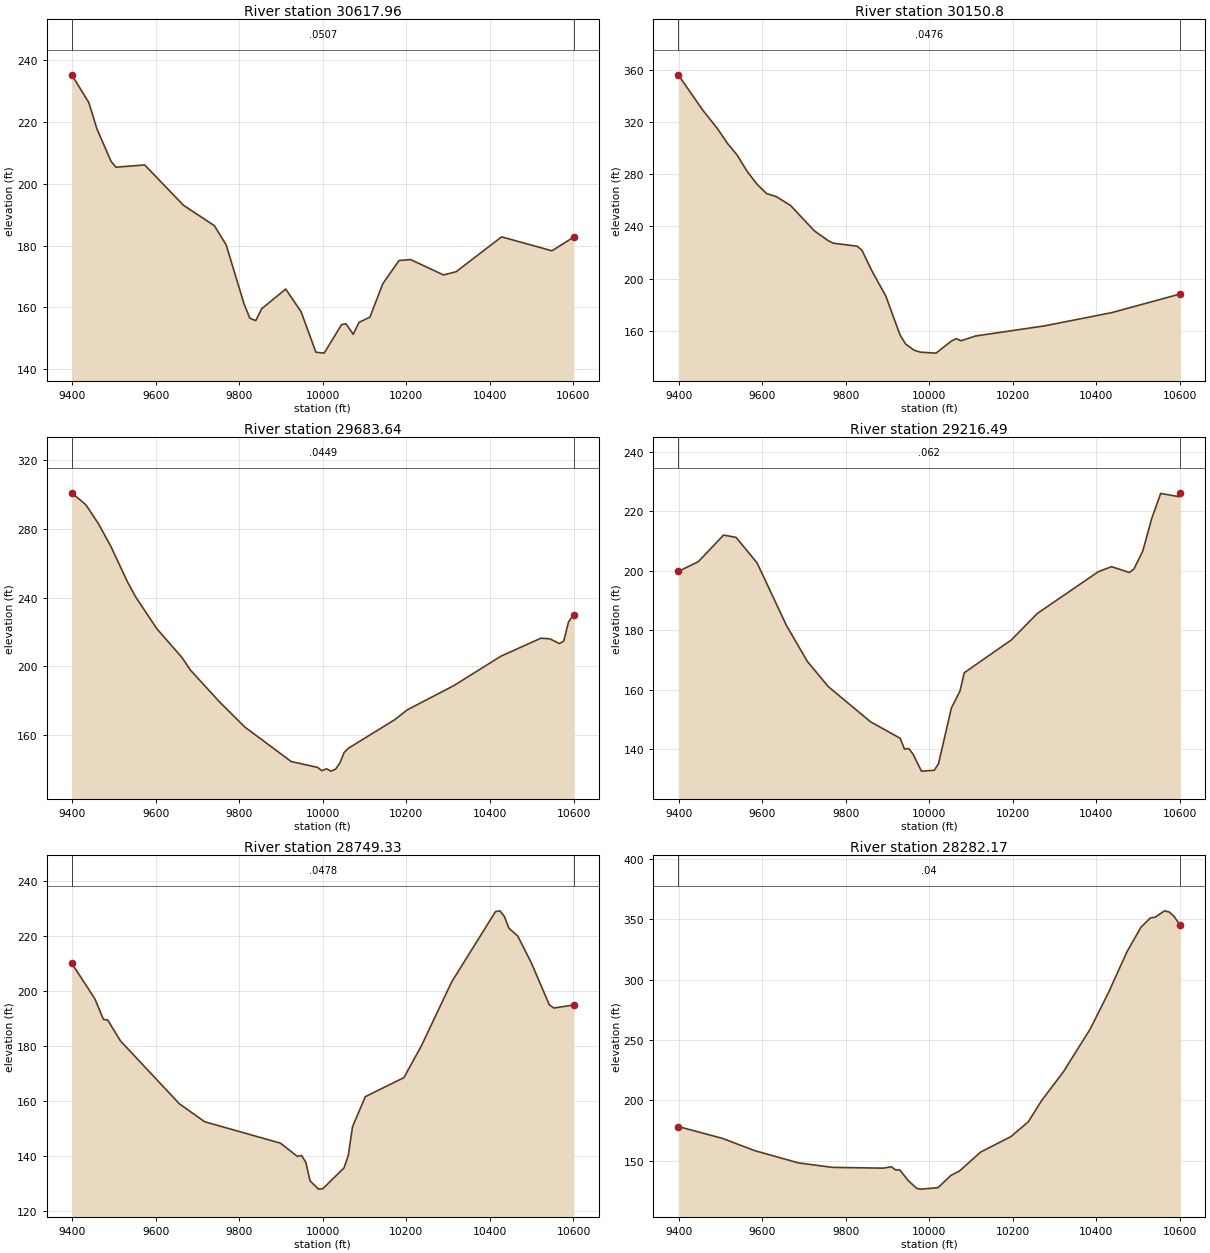
Type RM Length L Ch R = 1 ,30617.96,467.158000,467.158000,467.158000
XS GIS Cut Line= 6
529385.615184022735095.335291066529169.304875738 735292.58516659
528879.874407115735588.984142008528777.290973939735688.225530035
528632.181229933735812.703616117528501.897258758735907.067414579
#Sta/Elev= 30
9399.025235.30499439.771226.36169459.132217.87029493.008 207.3169504.594205.4106
9573.649 206.1329666.282193.09489740.384186.47339768.697180.24969811.166 161.244
9825.323156.53249839.479155.72679853.635159.58479911.217165.94999947.872158.6406
9983.476 145.50210003.28145.209710044.98154.457510055.54154.702510072.78151.3056
10086.68155.161510112.89156.879310143.53167.658510182.46175.186110210.29175.4975
 10288.9170.518710319.15171.561910427.99 182.84910548.59 178.34510600.97182.7983
#Mann= 3 , 0 , 0
9399.025  0.0507       09399.025  0.0507       010600.97  0.0507       0
#XS Ineff= 2 , 0
       09908.081                       0
Bank Sta=9399.025,10600.97
Exp/Cntr=0.3,0.1

Type RM Length L Ch R = 1 , 30150.8,467.158100,467.158100,467.158100
XS GIS Cut Line= 6
528885.545137041734728.428346824528806.508184335734841.563976341
528631.335712529735155.204969152528521.563208312 735322.46873604
528373.668176992735632.441387597528291.897680892735770.918153134
#Sta/Elev= 30
9399.042356.12739456.996329.41469493.104 314.8059517.177303.47419540.107294.6389
9564.245281.97779587.398 272.3859610.552 265.1319633.705262.80079668.128 255.927
9724.931236.52659759.012228.81769770.372227.07759827.249224.78639838.735221.7439
9861.705206.43889896.162186.42449927.076159.30469931.597155.83529943.411149.7789
9963.905144.99389979.672143.522610016.21142.806110052.73152.004710064.42153.8972
10076.12152.323810110.63155.918310276.83163.752810437.06173.862510600.95188.1915
#Mann= 3 , 0 , 0
9399.042  0.0476       09399.042  0.0476       010600.95  0.0476       0
#XS Ineff= 2 , 0
       0                               0
Bank Sta=9399.042,10600.95
Exp/Cntr=0.3,0.1

Type RM Length L Ch R = 1 ,29683.64,467.158100,467.158100,467.158100
XS GIS Cut Line= 6
528091.657001342734611.523628318528088.098091613 735006.17568039
528152.201372949735283.128406127 528159.43146191735408.562754706
528128.522619718735599.991332417528054.473718144735786.274651919
#Sta/Elev= 30
9399.104301.1415 9432.66294.24319462.731283.23389492.802269.87679532.862248.9999
9552.869240.11299602.886221.8705 9662.89205.11449682.891197.83029752.984179.1754
9813.178164.60189924.448144.43779987.026141.07099997.935139.097810008.82140.2269
10019.61138.858710030.39139.990110040.71143.523810050.99149.731710061.27152.1905
10172.14168.856210202.15174.5912 10312.9188.633510426.34205.880910522.01216.3813
10543.92215.981210566.11213.2225 10576.5214.6301 10588.3226.060510600.81230.1686
#Mann= 3 , 0 , 0
9399.104  0.0449       09399.104  0.0449       010600.81  0.0449       0
#XS Ineff= 2 , 0
       0                               0
Bank Sta=9399.104,10600.81
Exp/Cntr=0.3,0.1

Type RM Length L Ch R = 1 ,29216.49,467.158100,467.158100,467.158100
XS GIS Cut Line= 6
527737.828671122734576.889681799527704.628701455  734950.0732879
  527666.4050573735182.199473159527589.014373561735495.478172629
527546.767826712735624.052161425527496.561317115735748.108950878
#Sta/Elev= 30
9399.026199.79369447.306203.10779507.518212.05429537.624211.27319587.801202.6724
9658.048181.62129708.287169.47249758.544160.97639859.451149.17019930.422143.5926
  9940.6139.97149950.778140.15659960.956138.32089981.312132.549610011.89132.8301
10022.15135.069110052.94 153.79910073.47159.515110083.73165.673710196.62176.7573
10258.77185.660310404.66199.716510436.39201.410610478.87199.4594 10489.6200.5416
10511.07206.652810532.53217.618610554.02226.073610597.59224.984110600.97226.2785
#Mann= 3 , 0 , 0
9399.026   0.062       09399.026   0.062       010600.97   0.062       0
#XS Ineff= 2 , 0
       0                               0
Bank Sta=9399.026,10600.97
Exp/Cntr=0.3,0.1

Type RM Length L Ch R = 1 ,28749.33,467.158000,467.158000,467.158000
XS GIS Cut Line= 6
 527298.53501871734491.217509543527274.364195164734605.581842426
527223.266446714734998.385309585527182.973118652735219.563973564
527116.989344847 735455.71130733527036.760365768735659.059898863
#Sta/Elev= 30
9399.019210.11689454.433197.14559474.843189.70859484.989189.51289515.426181.9266
9656.609 159.0499717.115152.53019898.631144.73529939.078139.93219949.204140.2682
 9959.33137.76279969.455131.03119989.706128.03659999.833128.1608 10050.7135.7428
 10060.9140.203210071.11150.707610101.72161.635710194.14168.557110235.37179.9303
10308.32203.289310413.43228.902510424.07229.162610434.71227.085910445.36222.8783
10466.64220.008310498.81210.377310542.24195.0191 10553.1193.847410600.94194.9478
#Mann= 3 , 0 , 0
9399.019  0.0478       09399.019  0.0478       010600.94  0.0478       0
#XS Ineff= 2 , 0
       0                10101.28       0
Bank Sta=9399.019,10600.94
Exp/Cntr=0.3,0.1

Type RM Length L Ch R = 1 ,28282.17,467.158100,467.158100,467.158100
XS GIS Cut Line= 6
526931.777267478734447.982583981526881.538347392734494.228309762
526821.620909811734611.399099129526704.547172669735203.076951462
526645.367856896735374.752119581526550.529058516735568.290903143
#Sta/Elev= 30
9399.019178.38559504.515168.60329582.296158.39939686.434  148.329767.837144.5789
9889.126143.92869909.336145.07269919.441142.41159929.553142.42319949.824133.5137
9970.094127.1504 9980.23126.563110020.86127.739710051.49137.8378 10071.9141.4565
10123.06157.261310195.29170.024710237.11182.318210268.57199.709810321.34223.8283
10385.56259.286110429.37289.515510473.19322.990610506.76343.364510529.37351.0825
10540.68351.657210563.29356.929110574.59355.9455 10585.9352.374910600.93344.8121
#Mann= 3 , 0 , 0
9399.019    0.04       09399.019    0.04       010600.93    0.04       0
#XS Ineff= 2 , 0
       0                               0
Bank Sta=9399.019,10600.93
Exp/Cntr=0.3,0.1

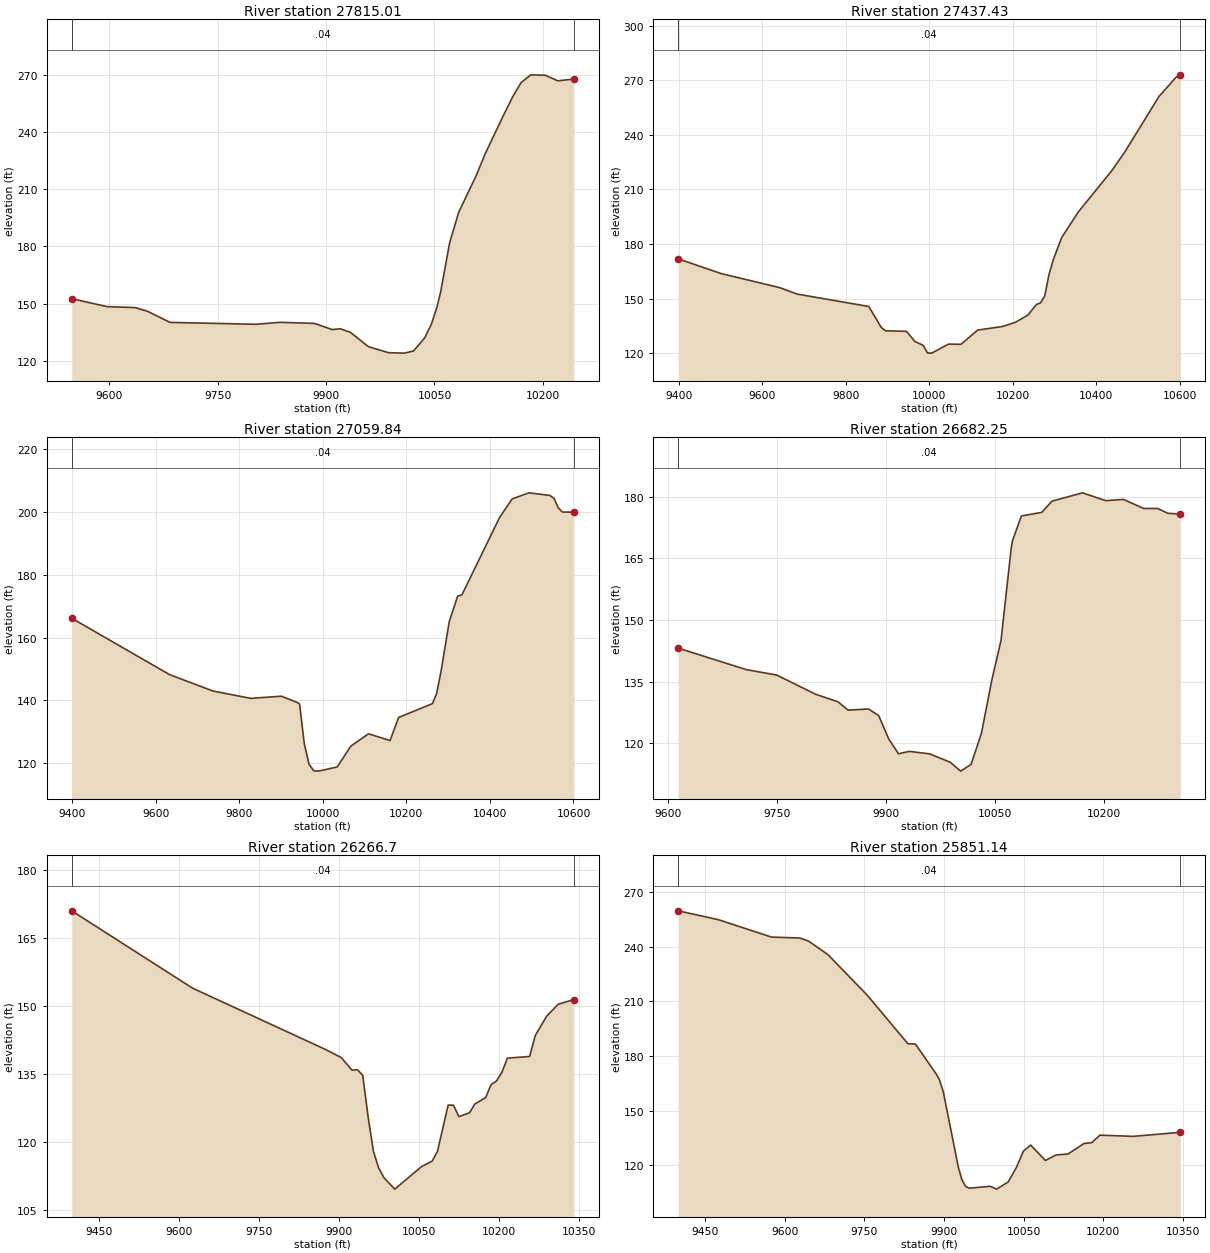
Type RM Length L Ch R = 1 ,27815.01,377.585800,377.585800,377.585800
XS GIS Cut Line= 2
 526567.77649796734556.093590394526151.299329728735112.731344074
#Sta/Elev= 30
 9547.78152.60329596.371148.42139635.876147.89639652.568145.98439683.795140.1342
9802.799139.14449836.184140.16659883.623139.60699908.601136.35819919.645 136.775
 9933.58134.92279958.558127.38979986.415124.227810008.51123.9981   10021125.1415
10036.49132.030210045.98139.419810053.18 147.86110058.47155.947410070.96181.8781
10083.45197.864210108.43217.742110119.95228.4479 10145.9249.137910158.39258.6254
10170.03266.062810183.36270.106610203.41269.885810220.83266.950710242.98267.8941
#Mann= 3 , 0 , 0
 9547.78    0.04       0 9547.78    0.04       010242.98    0.04       0
#XS Ineff= 2 , 0
       0                               0
Bank Sta=9547.78,10242.98
Exp/Cntr=0.3,0.1

Type RM Length L Ch R = 1 ,27437.43,377.585800,377.585800,377.585800
XS GIS Cut Line= 6
526829.671982663734448.695251705526610.800248423734539.590841564
526523.505393536734562.063206936526420.488823865734568.306501241
526075.534194101734550.618931023525654.666472197734611.490297921
#Sta/Elev= 30
9399.113171.82879501.307163.75749642.262155.95349683.875152.43629855.248145.6116
9885.302134.02229895.348132.25529945.577131.90599965.669126.3699 9985.76124.1704
9995.806120.021710005.84119.944210045.94124.894810075.96124.802510115.97132.6218
   10176134.6246 10206.1136.906410236.21140.883510256.28146.668510266.35147.6285
10276.44151.374610286.52163.0996 10296.6171.143910316.76  183.4310357.15197.7178
10438.15220.688810468.57230.793210549.84261.121810590.47271.645610600.97273.0683
#Mann= 3 , 0 , 0
9399.113    0.04       09399.113    0.04       010600.97    0.04       0
#XS Ineff= 2 , 0
       0                               0
Bank Sta=9399.113,10600.97
Exp/Cntr=0.3,0.1

Type RM Length L Ch R = 1 ,27059.84,377.585800,377.585800,377.585800
XS GIS Cut Line= 6
526730.515997623734330.542049578526515.646923269734167.068818913
526398.482209391734128.332476116526311.214084071734144.768382473
526043.140496989734251.849257814525617.550973468734290.356690383
#Sta/Elev= 30
9399.119166.15279633.264148.20839736.658143.00259827.838140.64159900.958141.3389
9939.677139.2924 9944.44138.86659955.725126.1872 9967.01119.71239978.295 117.595
 9989.58117.483210034.46118.817810067.17125.454510109.39129.362210161.01127.2253
10181.47134.570310262.51138.971910272.57142.230910282.63148.948210302.76165.1218
10322.88173.229910332.95173.571410423.22198.242210453.29204.143310493.34206.0811
 10543.4205.259210553.42204.319310563.43201.345210573.44199.963210600.93199.9344
#Mann= 3 , 0 , 0
9399.119    0.04       09399.119    0.04       010600.93    0.04       0
#XS Ineff= 2 , 0
       0                               0
Bank Sta=9399.119,10600.93
Exp/Cntr=0.3,0.1

Type RM Length L Ch R = 1 ,26682.25,415.556400,415.556400,415.556400
XS GIS Cut Line= 2
526471.666382253734107.579716936525979.102039039 733623.02455008
#Sta/Elev= 30
9614.239143.16759707.756137.94629749.839136.60969803.291131.94449834.004 130.118
9848.032128.07689876.087128.35429890.115126.73049904.143120.99739917.367117.4477
9932.198118.03469960.145117.43049988.664115.385810002.92113.225110017.18114.8573
10031.44122.3965 10045.7135.315510058.45145.064910072.47 167.47910074.22169.3031
 10086.5175.346710114.56176.229610128.58178.957610170.67180.980910202.56179.0696
10226.78179.379810254.83177.167110273.85177.179410288.11175.994210305.19175.8111
#Mann= 3 , 0 , 0
9614.239    0.04       09614.239    0.04       010305.19    0.04       0
#XS Ineff= 2 , 0
       0                               0
Bank Sta=9614.239,10305.19
Exp/Cntr=0.3,0.1

Type RM Length L Ch R = 1 , 26266.7,415.556300,415.556300,415.556300
XS GIS Cut Line= 6
526779.706162126734348.362255785526662.920612367734238.361973357
526594.074180914734118.279289036526578.226826839734024.828026478
526584.774079928733667.366826657 526531.02349532 733488.39782769
#Sta/Elev= 30
 9399.05171.05819625.292153.9763  9874.1 140.446 9904.18138.61779924.233135.8416
 9934.26 135.9519944.287134.69619954.313125.5892 9964.34 117.8979974.351114.1748
9984.351112.032510004.35109.554510054.35114.522810074.35 115.74510084.35117.9013
10104.37128.124510114.38128.0932 10124.4125.576110144.43126.435310154.46 128.376
10174.65129.785810184.78132.658910194.99133.4593 10205.2135.388910215.41138.5004
10257.02138.872810267.67143.529510288.97147.768210310.64150.414410339.89151.4484
#Mann= 3 , 0 , 0
 9399.05    0.04       0 9399.05    0.04       010339.89    0.04       0
#XS Ineff= 2 , 0
       0                10335.55       0
Bank Sta=9399.05,10339.89
Exp/Cntr=0.3,0.1

Type RM Length L Ch R = 1 ,25851.14,415.556400,415.556400,415.556400
XS GIS Cut Line= 6
 527314.18832663734147.914879105527144.548954291733899.470445482
527055.308826578733784.430544626526986.979875949 733712.08107019
526856.503574411733601.178036487526707.780627188  733427.3610312
#Sta/Elev= 30
9399.057 259.6649475.239254.76199574.956245.24519628.157244.72629644.762243.0415
9681.088 235.6549755.316213.34469831.916186.70829845.983186.57599884.951170.2664
 9891.06167.17429898.583160.43489926.828119.16089933.715112.02689940.951108.3485
9947.688 107.4039986.709108.48459999.052106.900310021.04110.851810036.66118.9328
10049.58127.739610063.39131.101410091.02122.629710111.03125.649210133.77126.1907
10163.68131.921310178.68132.441510193.86136.5351 10256.2135.866510345.36138.0792
#Mann= 3 , 0 , 0
9399.057    0.04       09399.057    0.04       010345.36    0.04       0
#XS Ineff= 2 , 0
       0                               0
Bank Sta=9399.057,10345.36
Exp/Cntr=0.3,0.1

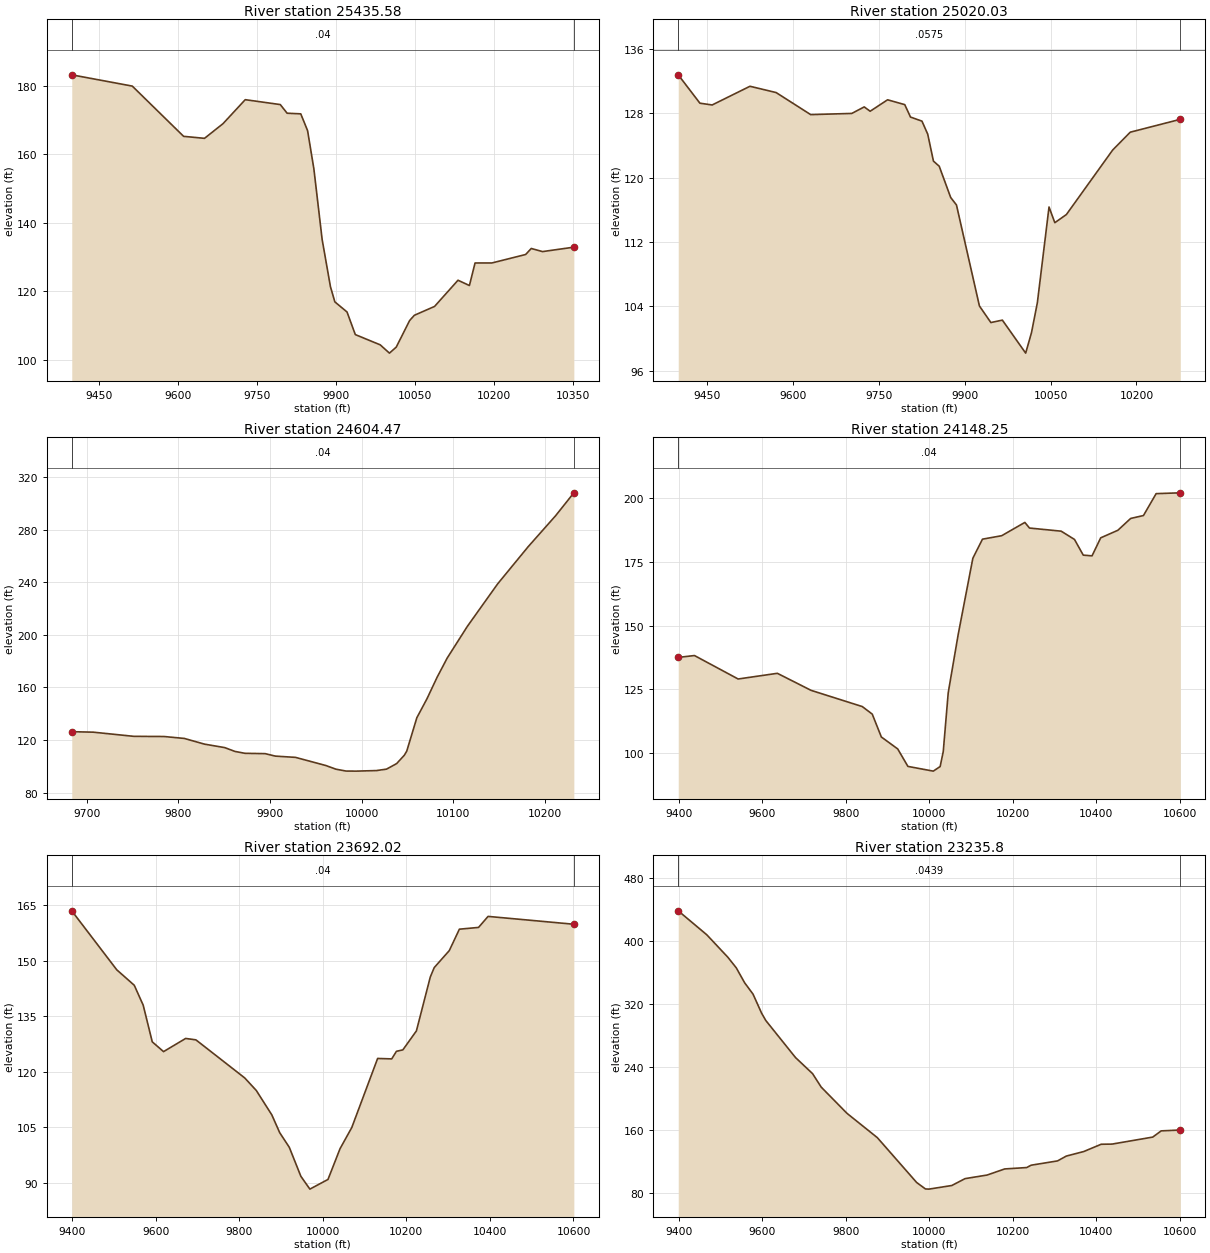
Type RM Length L Ch R = 1 ,25435.58,415.556300,415.556300,415.556300
XS GIS Cut Line= 6
527642.176565357733837.290783144527561.255221317733690.234725547
527493.249898777733607.222749765527418.539121663733536.599775741
527188.271429783733351.848542416526930.441116029 733244.87999084
#Sta/Elev= 30
9399.069183.1986 9513.96179.90889611.388165.24479651.059164.65969686.176168.9422
9728.391175.94639794.937174.51519807.885171.99179833.781171.80989846.728166.9203
9858.639155.80129874.381135.12719890.124121.37199898.519116.92329921.609113.9748
9937.363107.3784 9984.58104.390710002.15101.9693 10015.1103.734310040.38111.4642
10049.48113.022110087.76115.594610132.27123.243510153.94121.701610164.63128.2797
10196.65128.2861 10260.7 130.75910271.38132.515310292.73131.604510352.19132.8944
#Mann= 3 , 0 , 0
9399.069    0.04       09399.069    0.04       010352.19    0.04       0
#XS Ineff= 2 , 0
       0                 10323.6       0
Bank Sta=9399.069,10352.19
Exp/Cntr=0.3,0.1

Type RM Length L Ch R = 1 ,25020.03,415.556400,415.556400,415.556400
XS GIS Cut Line= 6
527663.466225935733300.376462214527576.944430118733119.713069799
527508.021949376 733049.43620082527436.308692179733031.307535454
527252.109221227733041.361102592526940.717017667732977.688514681
#Sta/Elev= 30
9399.122132.78139437.008129.25789458.427129.03619524.513131.35919570.215130.5784
9630.657127.83659702.482127.98449724.217128.79419734.593128.25729765.053 129.679
9795.095129.07799805.097127.53669825.161127.02629835.212125.41239845.262122.0559
9855.313 121.4279875.414117.53379885.464116.61459925.601104.06229945.604102.0014
9965.727 102.30310006.4498.2022210016.65100.756710026.87104.463510047.27116.3594
10057.39114.409610077.62115.421410158.56123.441410189.28125.655710276.75127.2514
#Mann= 3 , 0 , 0
9399.122  0.0575       09399.122  0.0575       010276.75  0.0575       0
#XS Ineff= 2 , 0
       0                 10212.9       0
Bank Sta=9399.122,10276.75
Exp/Cntr=0.3,0.1

Type RM Length L Ch R = 1 ,24604.47,456.224100,456.224100,456.224100
XS GIS Cut Line= 2
527488.831773847732986.295033276527256.565660775 732489.72610195
#Sta/Elev= 30
9683.611126.3391 9707.12125.9682 9751.28122.79889784.399122.66869806.479121.2043
9828.559116.86549850.638 114.2269861.678111.34629872.718109.88559894.798 109.636
9905.838107.76449927.917106.79669961.037 100.6049972.07797.806579983.11796.39221
9994.15696.3384610016.2496.7619210027.2897.8589810038.32102.059910046.69108.4099
10049.36111.5234 10060.4136.952510071.44151.359410082.48167.676510093.52182.3327
10115.59206.496810148.71238.846210181.83266.946110211.91290.616410231.82308.0273
#Mann= 3 , 0 , 0
9683.611    0.04       09683.611    0.04       010231.82    0.04       0
#XS Ineff= 2 , 0
       0                               0
Bank Sta=9683.611,10231.82
Exp/Cntr=0.3,0.1

Type RM Length L Ch R = 1 ,24148.25,456.224000,456.224000,456.224000
XS GIS Cut Line= 6
527694.460751565733402.585679284527627.552734223733175.194199714
527629.106589658733085.797279287 527897.45360493732628.825136462
527952.881487324732466.003756151527979.615934108 732297.40673625
#Sta/Elev= 30
9399.032137.47999437.918138.20939542.431128.9814 9636.33131.21769716.998124.5181
9839.615 118.1339863.501115.16149885.233106.17029924.421101.46849948.86794.59106
10009.6192.7345210026.0294.5344310033.45100.446310045.36123.6023 10069.2146.4893
10104.29  176.4910127.35183.998410173.29185.3513 10228.8190.5867 10239.9188.3738
 10315.7187.142510347.59183.890410368.59177.717110389.59177.427110410.36184.5192
10451.47187.497410482.11192.152910512.72 193.29510543.01201.908110600.92202.2285
#Mann= 3 , 0 , 0
9399.032    0.04       09399.032    0.04       010600.92    0.04       0
#XS Ineff= 2 , 0
       0                               0
Bank Sta=9399.032,10600.92
Exp/Cntr=0.3,0.1

Type RM Length L Ch R = 1 ,23692.02,456.224100,456.224100,456.224100
XS GIS Cut Line= 6
527806.944056767733651.119606398527840.701922167733494.288212146
527890.069119196733397.097124453528280.296655307732969.905691345
528376.215598022732804.901249262528425.618664488732652.056296624
#Sta/Elev= 30
9399.069163.40889506.822147.49659548.679143.33529570.038137.97069591.764128.0751
9618.782125.44129671.718128.9934 9696.26128.61249812.995118.35459840.751114.9677
9878.015108.37059896.798103.58899919.77599.639729947.47391.816019969.07288.35888
10012.4390.9740110041.21 99.252710069.36104.973710131.23 123.59810164.95123.4806
10176.27125.524410191.61 125.91210224.03131.024810257.29145.561210266.76148.1095
10302.85152.6964 10326.9158.455510372.76158.933710395.59161.903410600.91159.7892
#Mann= 3 , 0 , 0
9399.069    0.04       09399.069    0.04       010600.91    0.04       0
#XS Ineff= 2 , 0
       0                               0
Bank Sta=9399.069,10600.91
Exp/Cntr=0.3,0.1

Type RM Length L Ch R = 1 , 23235.8,456.224100,456.224100,456.224100
XS GIS Cut Line= 6
 528323.56731775734053.369738729528339.146516182733871.070456684
528374.859921196733693.113042764528425.929348593733512.378356219
528565.550835979733086.294345824528607.093798781732889.768130935
#Sta/Elev= 30
9399.033438.27529467.483407.85049517.726379.46299537.874366.04339558.023 347.011
9578.171332.5631 9598.46308.64249608.621299.2057 9679.75252.1933 9720.72231.7156
9741.233214.7213 9803.11181.38169875.725150.57269969.77293.709949990.782 85.5357
    999985.2944110054.0189.8935110085.6598.6031810138.37103.152910180.55110.8932
10233.28112.665810243.82115.637810307.05121.086310327.99127.193910369.86132.9823
10411.58142.212610437.53142.408110534.95151.296910555.19159.164610600.97 160.269
#Mann= 3 , 0 , 0
9399.033  0.0439       09399.033  0.0439       010600.97  0.0439       0
#XS Ineff= 2 , 0
       0                               0
Bank Sta=9399.033,10600.97
Exp/Cntr=0.3,0.1