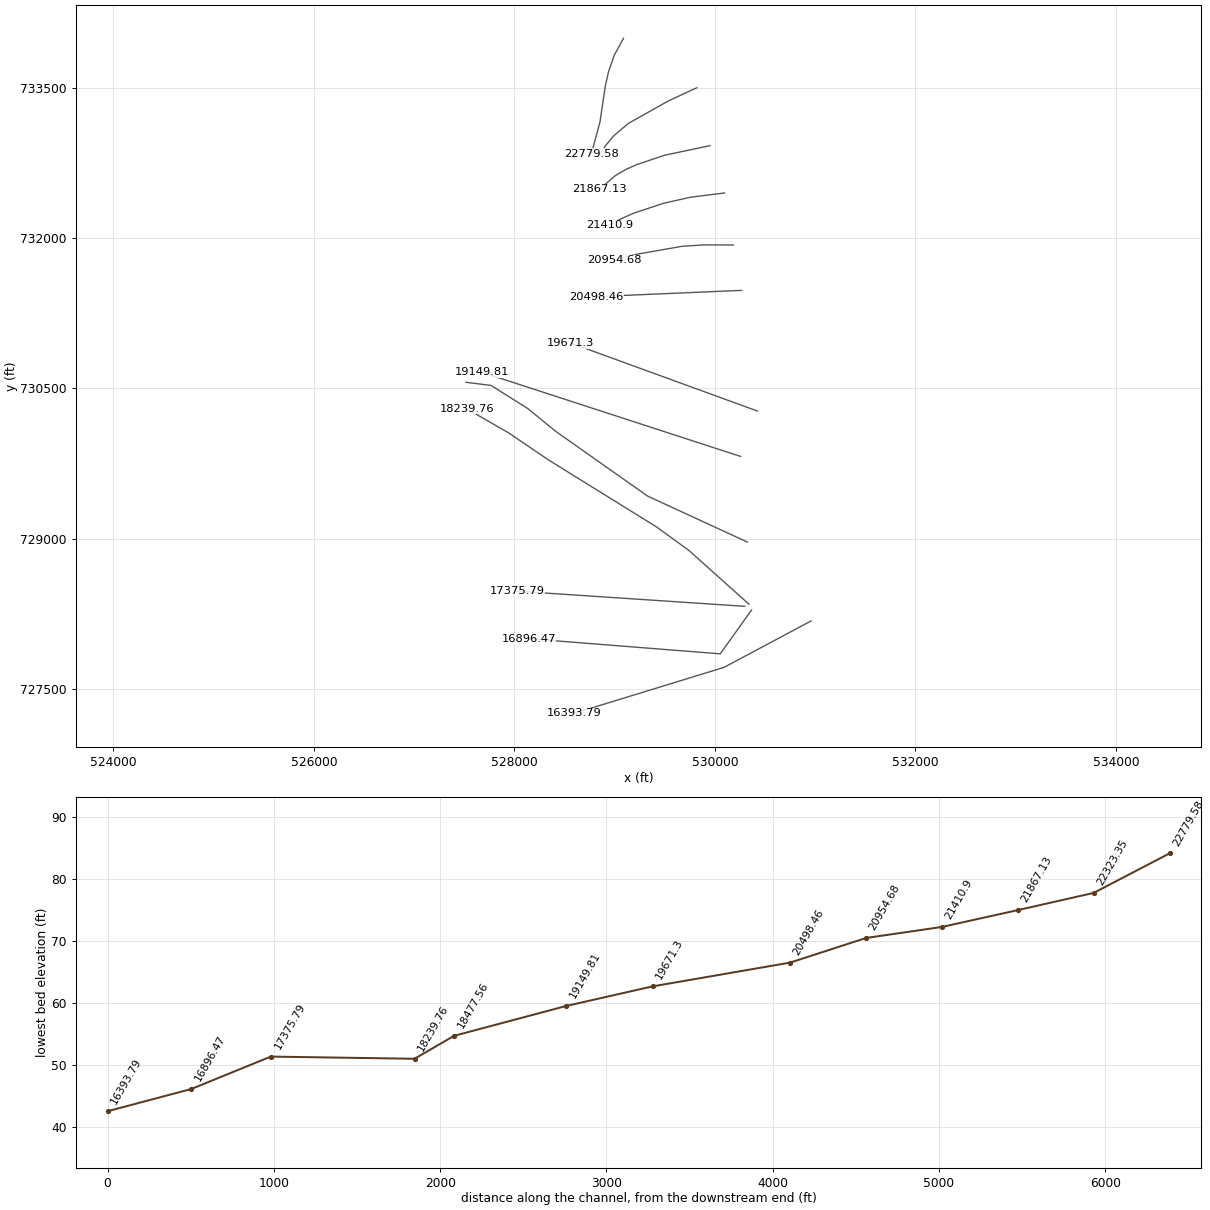
HEC-RAS study 1552_ras.prj: 1552

--- 1552_ras.g01 (geometry) --- (continued)

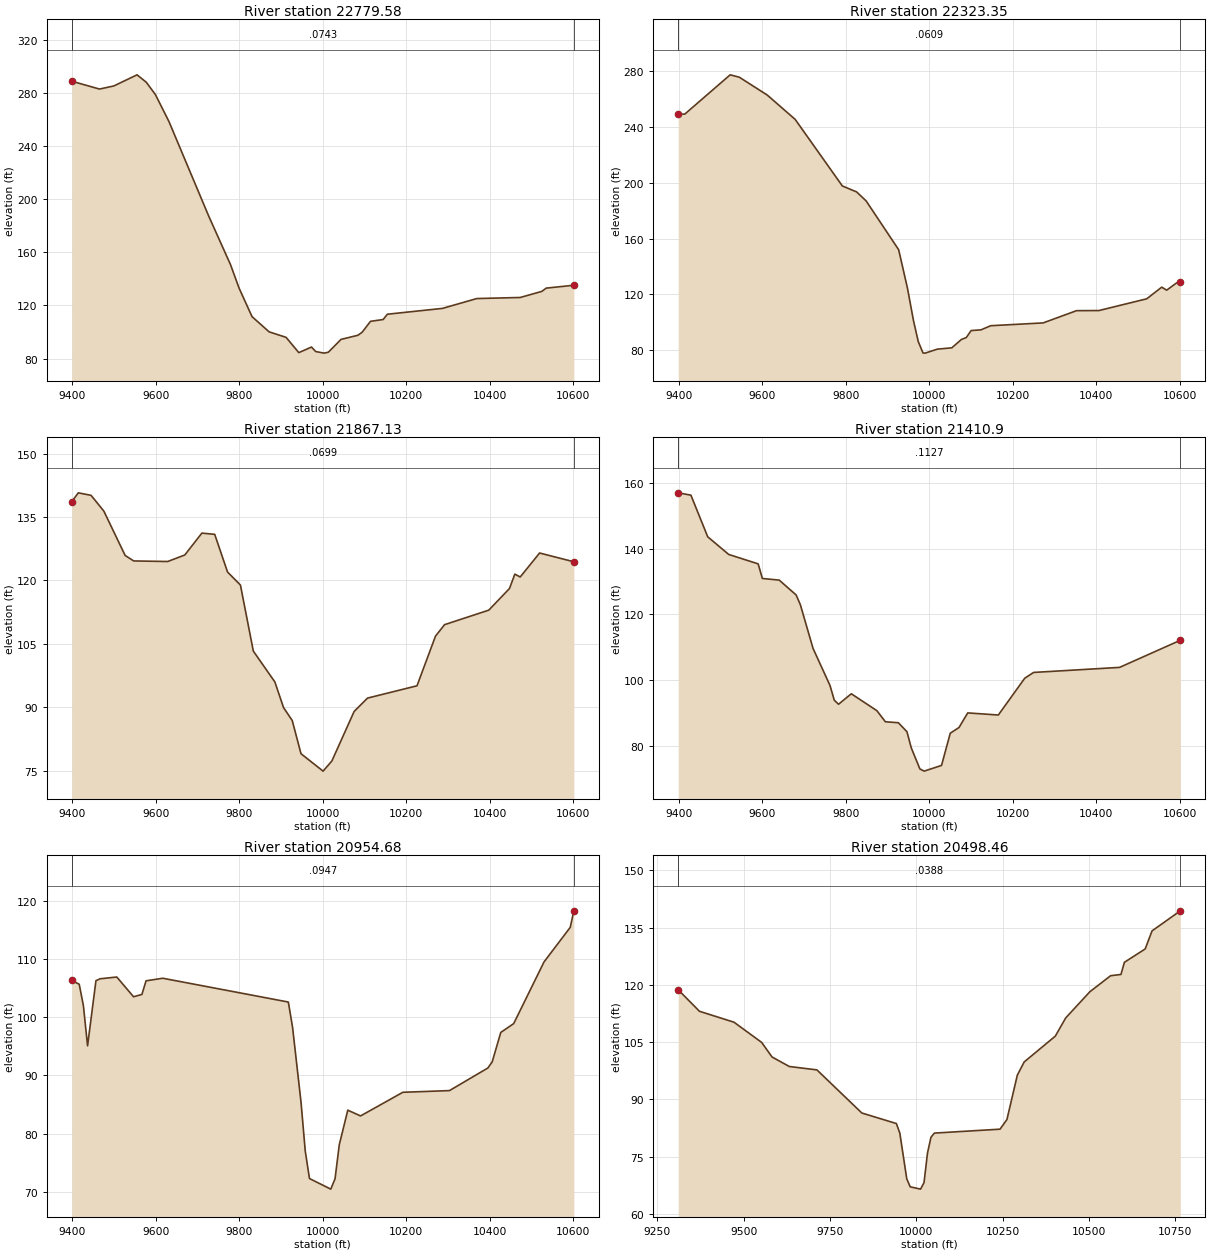
Type RM Length L Ch R = 1 ,22779.58,456.224000,456.224000,456.224000
XS GIS Cut Line= 6
529087.609025404733991.082931674528995.547576385733822.044465722
528938.014629984733656.353665789528905.017948997733506.406626897
528853.553243204733157.551099328528767.952734536732841.737070538
#Sta/Elev= 30
9399.076289.09629465.499283.1789 9499.86285.53789555.399293.91079577.526288.3082
9599.392278.96659631.473258.86959726.941187.3868 9779.05 150.8469799.665133.0319
9830.588111.61779871.424 100.1539912.17995.972839942.59584.466969972.95188.68129
 9983.0785.27628 10003.384.09121 10013.484.8117510043.6594.4471410083.9897.55898
10094.0699.7922310114.22108.063710144.46109.424510154.55113.419410286.52117.8234
10368.71125.235310472.58 126.042 10524.4130.650110534.85133.094910600.96135.2727
#Mann= 3 , 0 , 0
9399.076  0.0743       09399.076  0.0743       010600.96  0.0743       0
#XS Ineff= 2 , 0
       0                               0
Bank Sta=9399.076,10600.96
Exp/Cntr=0.3,0.1

Type RM Length L Ch R = 1 ,22323.35,456.224100,456.224100,456.224100
XS GIS Cut Line= 6
529819.314797395733498.132599507529534.174192576733366.206100761
 529135.98233254733142.417537684528989.087370874733016.887812295
528912.071772426732924.791696559528847.224854083732827.467527067
#Sta/Elev= 30
 9399.04249.45339414.613249.35939523.398277.5939 9545.25 275.8919612.113 263.073
9678.977245.59539791.903197.7839 9825.98193.51149848.697187.09799926.711 152.003
9947.795124.35549962.287100.94429973.64586.008259985.004 77.83629989.96377.71472
10019.1980.5691810053.9181.5214210077.0687.5513210088.6388.9021510100.2193.92688
10123.8494.4366310147.0797.3982710272.5299.4158210352.51108.205210406.18108.3011
10520.51116.715610556.47125.091510568.32122.935910592.02128.138710600.94128.5499
#Mann= 3 , 0 , 0
 9399.04  0.0609       0 9399.04  0.0609       010600.94  0.0609       0
#XS Ineff= 2 , 0
       0                               0
Bank Sta=9399.04,10600.94
Exp/Cntr=0.3,0.1

Type RM Length L Ch R = 1 ,21867.13,456.224100,456.224100,456.224100
XS GIS Cut Line= 6
529950.399125782732920.562670025529498.133720398  732825.2633062
529220.048882205732731.594068966529111.528776272732683.490588279
529002.648952788732619.210396723528851.880185484732487.180758664
#Sta/Elev= 30
9399.019138.63919414.711140.72229445.282140.12659475.852136.39979526.803125.9196
9547.183124.62319628.705124.48719669.592126.02979710.524131.20339741.223 130.908
9771.959121.99719802.806118.92099833.653103.31679885.25996.015629905.99189.95706
9926.79686.905959947.75879.0597410000.6874.93991 10021.777.34108   1007589.04486
10106.9792.2001110225.4895.1112210269.78106.856510291.48109.559810397.36112.9905
 10446.9118.109410459.72121.506910472.54120.832610518.97126.497310600.95124.4246
#Mann= 3 , 0 , 0
9399.019  0.0699       09399.019  0.0699       010600.95  0.0699       0
#XS Ineff= 2 , 0
       0                               0
Bank Sta=9399.019,10600.95
Exp/Cntr=0.3,0.1

Type RM Length L Ch R = 1 , 21410.9,456.224000,456.224000,456.224000
XS GIS Cut Line= 6
530095.202270082732448.835710914529755.336988721 732406.21322232
  529489.7668091732346.713421836529188.976168021 732247.12138521
529049.256001215732184.625121524528946.872502677732128.067837958
#Sta/Elev= 30
9399.039156.98849429.401156.27569469.613143.60039519.877138.21929590.352135.3529
9600.443130.90479640.807130.40219681.235125.88339691.362 122.9329721.744109.6098
9762.38698.303339772.57993.840679782.77292.59182 9813.3595.778739874.50790.64402
9895.00687.25487 9925.9486.970579946.56384.227649956.87479.326289977.49672.89843
9987.80872.2225410029.3573.9653110050.2783.7741510071.1885.50782 10092.189.95596
 10165.389.3136710228.56100.518910249.74102.281710455.52103.819810600.96112.0742
#Mann= 3 , 0 , 0
9399.039  0.1127       09399.039  0.1127       010600.96  0.1127       0
#XS Ineff= 2 , 0
       0                               0
Bank Sta=9399.039,10600.96
Exp/Cntr=0.3,0.1

Type RM Length L Ch R = 1 ,20954.68,456.224100,456.224100,456.224100
XS GIS Cut Line= 6
 530182.83366333731929.980169742 529889.16370649731931.137271871
529669.275873333 731916.63107729529225.463454171731838.485457182
529108.667370534731810.502402884528996.766825007731776.416218293
#Sta/Elev= 30
9399.039106.30649416.876105.65559426.877101.97629436.87895.069699456.881106.2596
9466.882106.59349506.888106.89539546.893103.50399566.895 103.8989576.896106.2434
9616.899106.68469917.498102.59539927.61898.249499947.85785.387029957.97676.98974
9968.09572.2663310019.0570.4432110029.2472.2066510039.4378.07314 10059.884.01334
10090.3583.0229710191.6587.0854610303.2487.37672 10395.291.2626110405.48  92.309
10426.0597.37452 10456.998.8835610529.62109.493410592.35115.434810600.95118.2711
#Mann= 3 , 0 , 0
9399.039  0.0947       09399.039  0.0947       010600.95  0.0947       0
#XS Ineff= 2 , 0
       09894.372                       0
Bank Sta=9399.039,10600.95
Exp/Cntr=0.3,0.1

Type RM Length L Ch R = 1 ,20498.46,827.159700,827.159700,827.159700
XS GIS Cut Line= 2
530266.373041481  731477.5288831528813.248041451  731415.0288831
#Sta/Elev= 30
9310.149118.68429371.579113.05999471.671110.19619551.745104.91259581.773101.0978
9631.81998.595179711.89397.703469842.01386.412579942.106 83.64869952.11581.14198
9972.13369.182399982.14367.0751410012.17 66.469510022.1868.1807410032.1975.89014
 10042.280.0260610052.21 81.148710242.3882.17324 10262.4 84.710410292.4396.31885
10312.45 99.795710402.53106.546910432.56111.308210502.62118.175610562.68122.3715
10592.71122.705710602.72125.892210662.77129.376310682.79134.120710764.62139.3713
#Mann= 3 , 0 , 0
9310.149  0.0388       09310.149  0.0388       010764.62  0.0388       0
#XS Ineff= 2 , 0
       0                               0
Bank Sta=9310.149,10764.62
Exp/Cntr=0.3,0.1

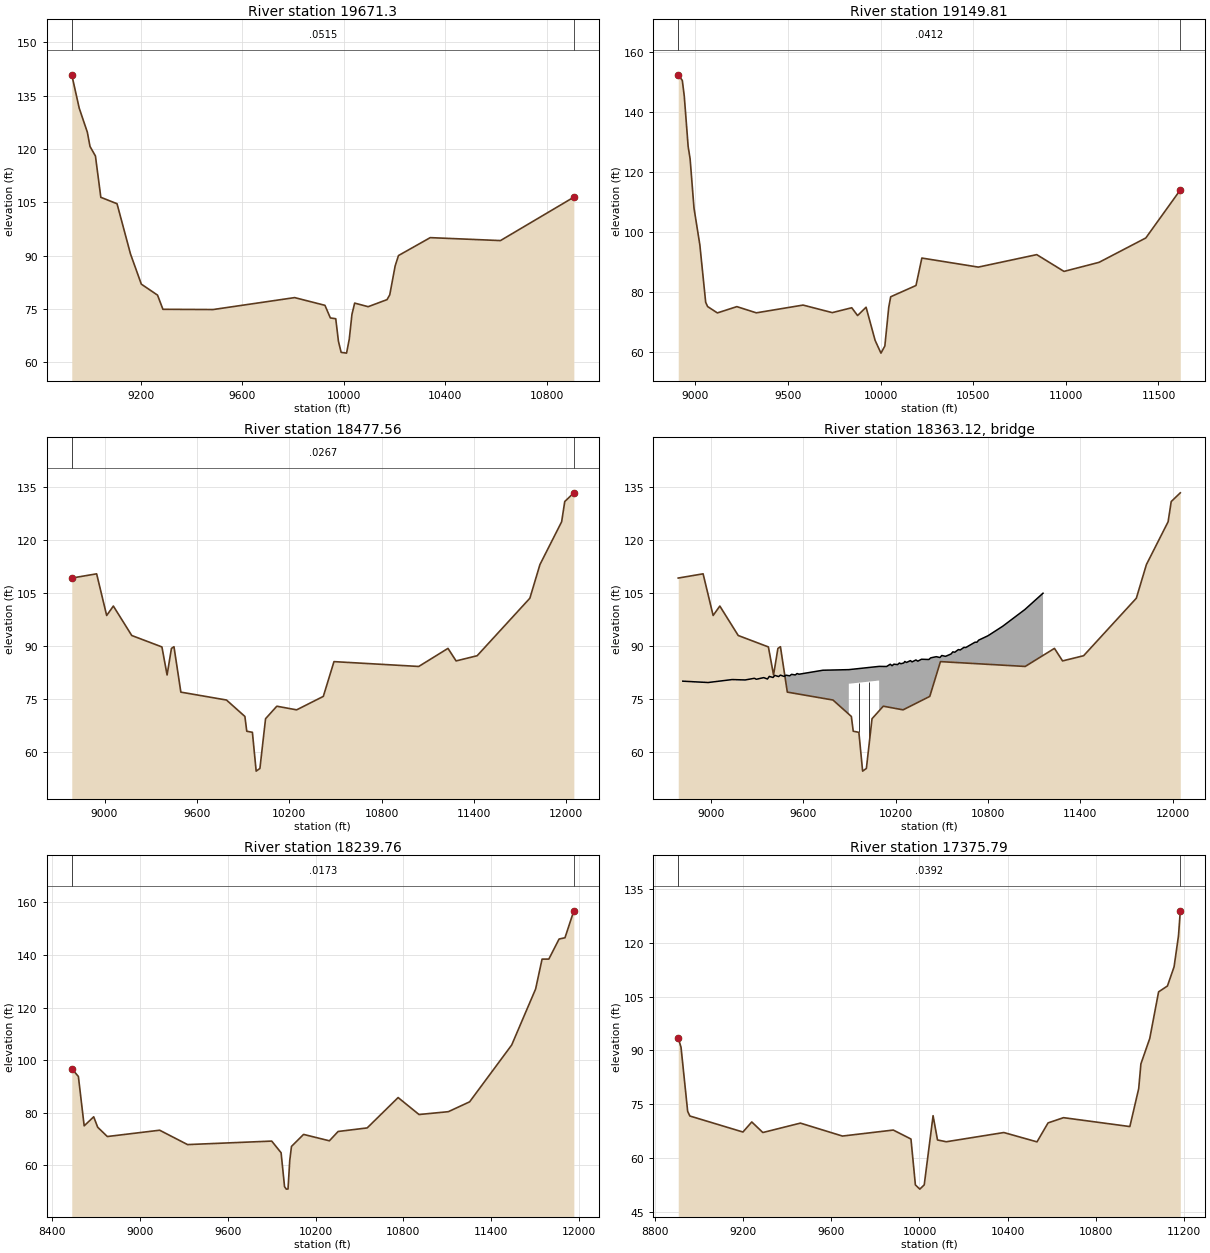
Type RM Length L Ch R = 1 , 19671.3,521.486300,521.486300,521.486300
XS GIS Cut Line= 2
530422.623041481730274.403883085528563.248041451730951.487216428
#Sta/Elev= 30
8927.232140.82388956.629 131.4498988.557124.71888999.199120.68989020.484118.0262
9041.768106.41039105.623104.60549158.83590.465659201.40482.011519265.25878.93095
9286.54374.946879484.26174.878289805.74278.232559925.08676.062039946.37172.52515
9967.65572.292619978.29865.93933 9988.9462.8541410010.2262.6328910020.8766.53353
10031.5173.5181610042.1576.6890310095.3675.6766910169.8677.66825 10180.5 79.0198
10201.7987.14065 10214.990.0476110340.1495.0819210616.8494.2525110906.05106.4523
#Mann= 3 , 0 , 0
8927.232  0.0515       08927.232  0.0515       010906.05  0.0515       0
#XS Ineff= 2 , 0
       0                               0
Bank Sta=8927.232,10906.05
Exp/Cntr=0.3,0.1

Type RM Length L Ch R = 1 ,19149.81,672.246800,672.246800,672.246800
XS GIS Cut Line= 2
530255.956374764729821.278883085527677.831374824730659.820549756
#Sta/Elev= 30
8906.793152.3936 8928.83150.51998939.346145.31038960.377128.44668970.893124.3443
8991.924107.88649023.47195.629849055.01876.433169065.53475.006799118.11272.88657
9223.26974.986699328.42572.915099580.80175.502659738.53572.984089843.69274.60929
9875.23972.008989921.07774.78707 9969.8863.7189210001.4359.4587410022.4661.83667
10043.4974.7671910054.01 78.279410190.7182.0441210222.2691.2093910527.2188.18717
10842.6892.35076 10989.986.7489211179.18 89.779111431.5697.9129311617.86113.9582
#Mann= 3 , 0 , 0
8906.793  0.0412       08906.793  0.0412       011617.86  0.0412       0
#XS Ineff= 2 , 0
       0                               0
Bank Sta=8906.793,11617.86
Exp/Cntr=0.3,0.1

Type RM Length L Ch R = 1 ,18477.56,237.804600,237.804600,237.804600
XS GIS Cut Line= 6
530323.664708108728967.112216413529328.873041451729425.445549756
528412.206374764730071.278883085528130.956374764730300.445549756
527766.373041451730529.612216428527516.373041451730560.862216428
#Sta/Elev= 30
8787.296109.31668948.873110.51649014.08598.718799057.559101.39079177.11393.05313
9373.14189.814349406.68281.876189434.896 89.38339451.40389.885829496.12577.01952
9792.667 74.78299912.24770.133249924.45465.948439961.07365.638289985.48654.65193
 10009.955.4146610046.5269.4899110119.7673.0331910248.53 72.000910421.8775.81044
10491.1785.6564511041.9984.2870511231.9689.4053111284.6285.8553611421.5187.32635
11764.04103.608811829.47113.134511970.56125.259311990.72130.9838 12049.8133.4492
#Mann= 3 , 0 , 0
8787.296  0.0267       08787.296  0.0267       0 12049.8  0.0267       0
#XS Ineff= 2 , 0
       09829.941        10173.59       0
Bank Sta=8787.296,12049.8
Exp/Cntr=0.3,0.1

Type RM Length L Ch R = 3 ,18363.12,,,
BEGIN DESCRIPTION:
END DESCRIPTION:
Bridge Culvert--1,0,-1,-1, 0
Deck Dist Width WeirC Skew NumUp NumDn MinLoCord MaxHiCord MaxSubmerge Is_Ogee
70.402300,97.000000,2.6,0, 60, 60, , , 0.95, 0, 0,0,,
 8817.01 8981.25 9137.93 9222.29 9282.55 9294.61 9342.81 9366.92 9378.97 9403.08
 9415.13 9439.23 9451.28 9475.39 9487.44 9511.55 9523.60 9547.70 9559.75 9571.81
 9727.07 9895.82 9895.8210092.8210092.8210141.2010164.8710176.7010188.5310212.20
10224.0310234.2110252.3010259.9210270.4010295.9110306.5910331.9110343.9110367.90
10415.9010427.8910463.8910487.8910499.8810523.8810559.9410571.8810583.8710607.87
10619.8710643.8710655.8610715.8610727.8610739.8510799.8510895.8311039.8111157.67
   80.12   79.74   80.58   80.47   80.94   80.66   81.13   80.73   81.47   81.17
   81.76   81.42   81.84   81.46   81.82   81.64   82.06   81.89   82.29   82.09
   83.22   83.39   83.39   84.31   84.31   84.28   84.92   84.50   84.94   84.81
   85.27   85.06   85.27   85.70   85.42   85.94   85.59   86.13   85.79   86.33
   86.26   86.72   87.06   86.82   87.40   87.15   87.82   88.43   88.31   89.07
   88.96   89.70   89.65   91.16   91.15   91.75   92.98   95.68  100.41  105.03
 -919.88 -920.26 -919.42 -919.53 -919.06 -919.34 -918.87 -919.27 -918.53 -918.83
 -918.24 -918.58 -918.16 -918.54 -918.18 -918.36 -917.94 -918.11 -917.71 -917.91
 -916.78 -916.61   79.39   80.31 -915.69 -915.72 -915.08 -915.50 -915.06 -915.19
 -914.73 -914.94 -914.73 -914.30 -914.58 -914.06 -914.41 -913.87 -914.21 -913.67
 -913.74 -913.28 -912.94 -913.18 -912.60 -912.85 -912.18 -911.57 -911.69 -910.93
 -911.04 -910.30 -910.35 -908.84 -908.85 -908.25 -907.02 -904.32 -899.59 -894.97
 8817.01 8981.25 9137.93 9222.29 9282.55 9294.61 9342.81 9366.92 9378.97 9403.08
 9415.13 9439.23 9451.28 9475.39 9487.44 9511.55 9523.60 9547.70 9559.75 9571.81
 9727.07 9897.51 9897.5110094.5110094.5110141.2010164.8710176.7010188.5310212.20
10224.0310234.2110252.3010259.9210270.4010295.9110306.5910331.9110343.9110367.90
10415.9010427.8910463.8910487.8910499.8810523.8810559.9410571.8810583.8710607.87
10619.8710643.8710655.8610715.8610727.8610739.8510799.8510895.8311039.8111157.67
   80.12   79.74   80.58   80.47   80.94   80.66   81.13   80.73   81.47   81.17
   81.76   81.42   81.84   81.46   81.82   81.64   82.06   81.89   82.29   82.09
   83.22   83.40   83.40   84.32   84.32   84.28   84.92   84.50   84.94   84.81
   85.27   85.06   85.27   85.70   85.42   85.94   85.59   86.13   85.79   86.33
   86.26   86.72   87.06   86.82   87.40   87.15   87.82   88.43   88.31   89.07
   88.96   89.70   89.65   91.16   91.15   91.75   92.98   95.68  100.41  105.03
 -919.88 -920.26 -919.42 -919.53 -919.06 -919.34 -918.87 -919.27 -918.53 -918.83
 -918.24 -918.58 -918.16 -918.54 -918.18 -918.36 -917.94 -918.11 -917.71 -917.91
 -916.78 -916.60   79.40   80.32 -915.68 -915.72 -915.08 -915.50 -915.06 -915.19
 -914.73 -914.94 -914.73 -914.30 -914.58 -914.06 -914.41 -913.87 -914.21 -913.67
 -913.74 -913.28 -912.94 -913.18 -912.60 -912.85 -912.18 -911.57 -911.69 -910.93
 -911.04 -910.30 -910.35 -908.84 -908.85 -908.25 -907.02 -904.32 -899.59 -894.97
Pier Skew, UpSta & Num, DnSta & Num=  ,9960.82, 2 ,9962.51, 2 , 0 , 0 , 0 ,,
    4.00    4.00
 -916.30   83.70
    4.00    4.00
 -916.30   83.70
Pier Skew, UpSta & Num, DnSta & Num=  ,10027.82, 2 ,10029.51, 2 , 0 , 0 , 0 ,,
    4.00    4.00
 -915.99   84.01
    4.00    4.00
 -915.98   84.02
BR Coef=-1 , 0 , 0 ,, 0 ,,,0.8,0,1,0,
WSPro=,,,, 1 ,,,, 0 ,,,, 0 ,,,,-1 ,-1 ,-1 , 0 , 0 , 0 , 0 , 0
BC Design=,, 0 ,, 0 ,,,,,,

Type RM Length L Ch R = 1 ,18239.76,863.966000,863.966000,863.966000
XS GIS Cut Line= 6
530339.289708108728347.320549771529740.331374764728883.778883085
529417.414708138729118.153883085528334.081374764729790.028883085
527943.456374794730055.653883085527526.789708108730295.237216428
#Sta/Elev= 30
8533.71196.769488578.92993.80209 8618.4975.021858683.55278.46927  8710.874.50212
8776.73570.958159134.28373.359739325.06167.892069900.14469.223269964.22164.78962
9987.84451.888969999.65650.9482410011.4750.9964510023.2861.7804310035.09 67.1905
10117.77 71.768510294.1969.3320510353.9572.8809510552.5174.2354110763.9685.78628
10906.8679.3283311107.3680.4153711252.4884.1580911540.01 105.78211703.47127.0856
11747.64138.452311793.78138.469311863.96   146.111904.09146.578911964.75156.8276
#Mann= 3 , 0 , 0
8533.711  0.0173       08533.711  0.0173       011964.75  0.0173       0
#XS Ineff= 2 , 0
       0 9825.69        10113.86       0
Bank Sta=8533.711,11964.75
Exp/Cntr=0.3,0.1

Type RM Length L Ch R = 1 ,17375.79,479.323100,479.323100,479.323100
XS GIS Cut Line= 2
530297.623041481728326.487216413528026.789708108728477.528883085
#Sta/Elev= 30
8906.48293.438388919.13390.90221  8949.273.014278959.22271.707919199.75267.23836
 9239.84 70.04729289.95167.099249460.32769.724569650.74666.113769881.25567.78638
9961.43165.282339981.47652.4844210001.5251.3041110021.5652.4884310061.6571.79388
 10081.765.0206710121.7864.5242710382.3667.0969410532.6964.49334 10582.869.78021
10652.9671.2437810953.6268.7618210993.7179.3465711003.7386.2609111043.8293.35115
11083.91106.349111123.99 107.98511154.06 113.336 11174.1121.996111182.33128.9579
#Mann= 3 , 0 , 0
8906.482  0.0392       08906.482  0.0392       011182.33  0.0392       0
#XS Ineff= 2 , 0
       09500.594        10610.07       0
Bank Sta=8906.482,11182.33
Exp/Cntr=0.3,0.1

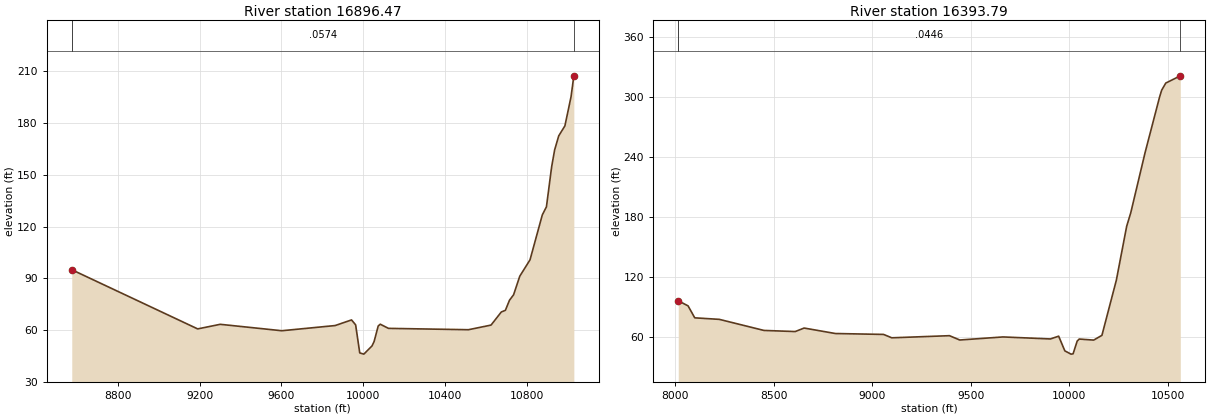
Type RM Length L Ch R = 1 ,16896.47,502.678400,502.678400,502.678400
XS GIS Cut Line= 3
530365.331374764728290.028883085530052.831374764  727852.5288831
528141.373041451728003.570549771
#Sta/Elev= 30
8575.18895.018019190.90760.68994 9301.2563.353449602.18559.629089862.99562.63479
9943.24565.894559963.30763.026799983.369 46.769610003.4346.0637610043.5650.85335
10053.5953.3729610073.6562.3958310083.6863.4089410123.81 61.005710515.0260.22013
10625.3662.9064210675.5270.4989510695.5871.4878210715.6477.3305810735.71 80.4888
 10765.891.2456110815.96100.754710876.14126.841110896.21131.476710921.45154.5094
10936.33164.503810956.39172.660610986.49178.418711016.58195.338411030.25207.4592
#Mann= 3 , 0 , 0
8575.188  0.0574       08575.188  0.0574       011030.25  0.0574       0
#XS Ineff= 2 , 0
       09117.597        10711.97       0
Bank Sta=8575.188,11030.25
Exp/Cntr=0.3,0.1

Type RM Length L Ch R = 1 ,16393.79,611.002800,611.002800,611.002800
XS GIS Cut Line= 3
530959.081374764728180.653883085530089.289708108727717.112216413
528594.498041451  727258.7788831
#Sta/Elev= 30
8014.86295.970538064.81390.815718098.80778.841318223.45377.315778450.08266.21768
8608.72365.098088654.048 68.61128812.68963.127919057.247 62.22559099.08558.83591
9391.95260.960389444.24956.632949663.89959.702649904.46857.684919946.30660.46907
9977.68545.7617610009.0642.4837210019.5242.7781410040.4455.59752 10050.957.58649
10124.1256.5422310165.9661.2943510239.17116.523710291.47170.447310312.39184.1291
10385.61244.783410458.82300.152210469.28306.9109 10490.2314.053710563.94321.3005
#Mann= 3 , 0 , 0
8014.862  0.0446       08014.862  0.0446       010563.94  0.0446       0
#XS Ineff= 2 , 0
       08924.918                       0
Bank Sta=8014.862,10563.94
Exp/Cntr=0.3,0.1