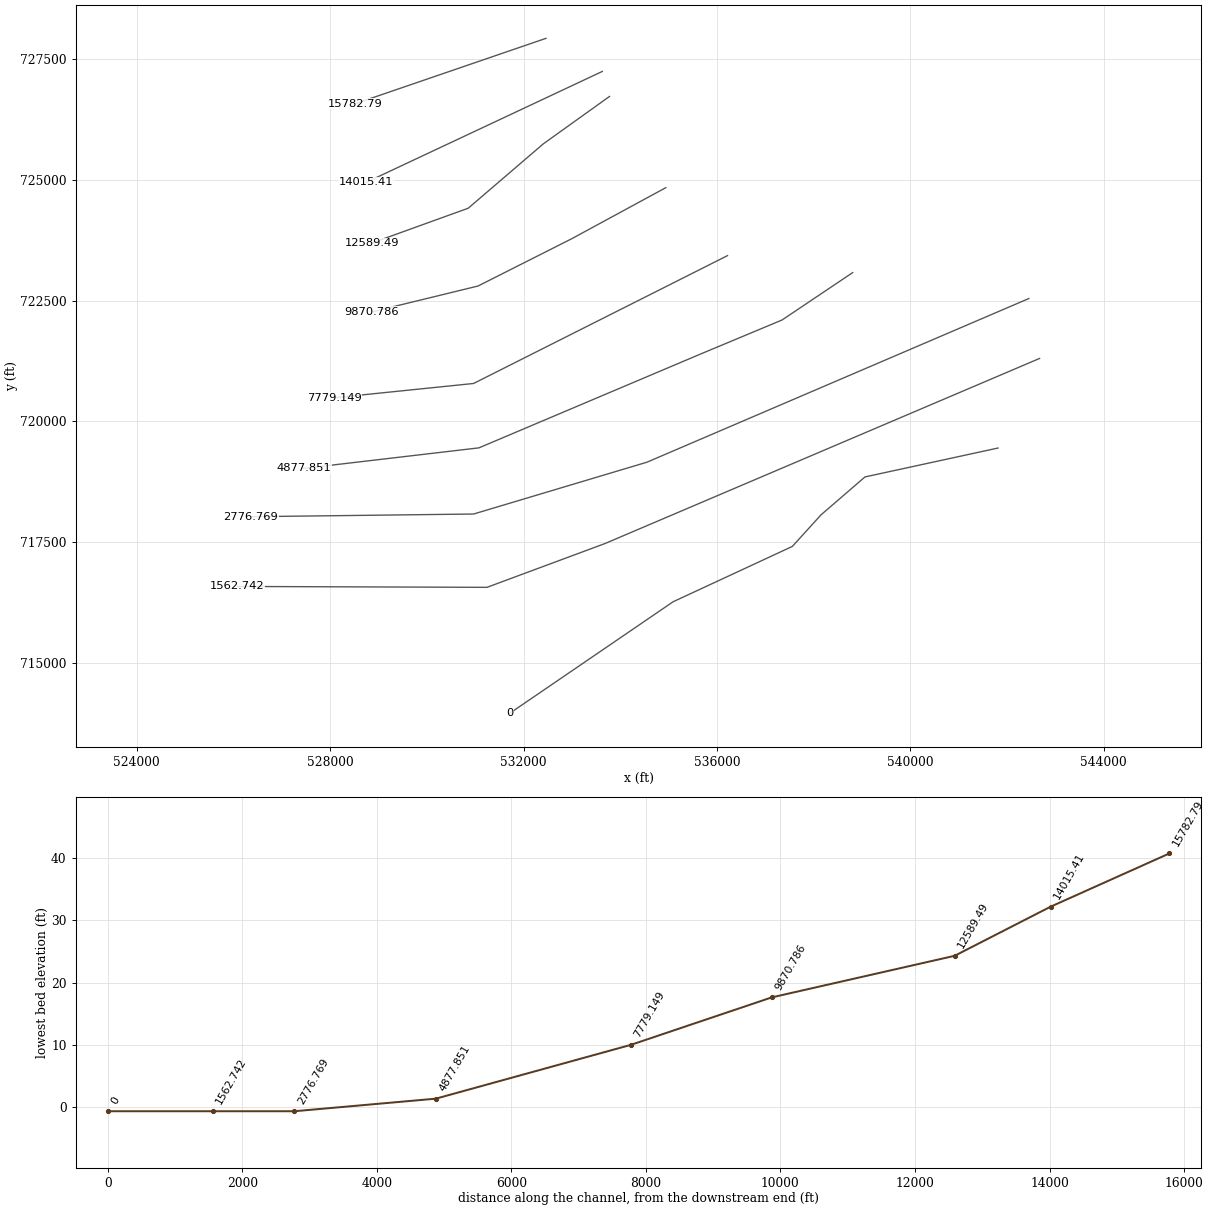
HEC-RAS study 1552_ras.prj: 1552

--- 1552_ras.g01 (geometry) --- (continued)

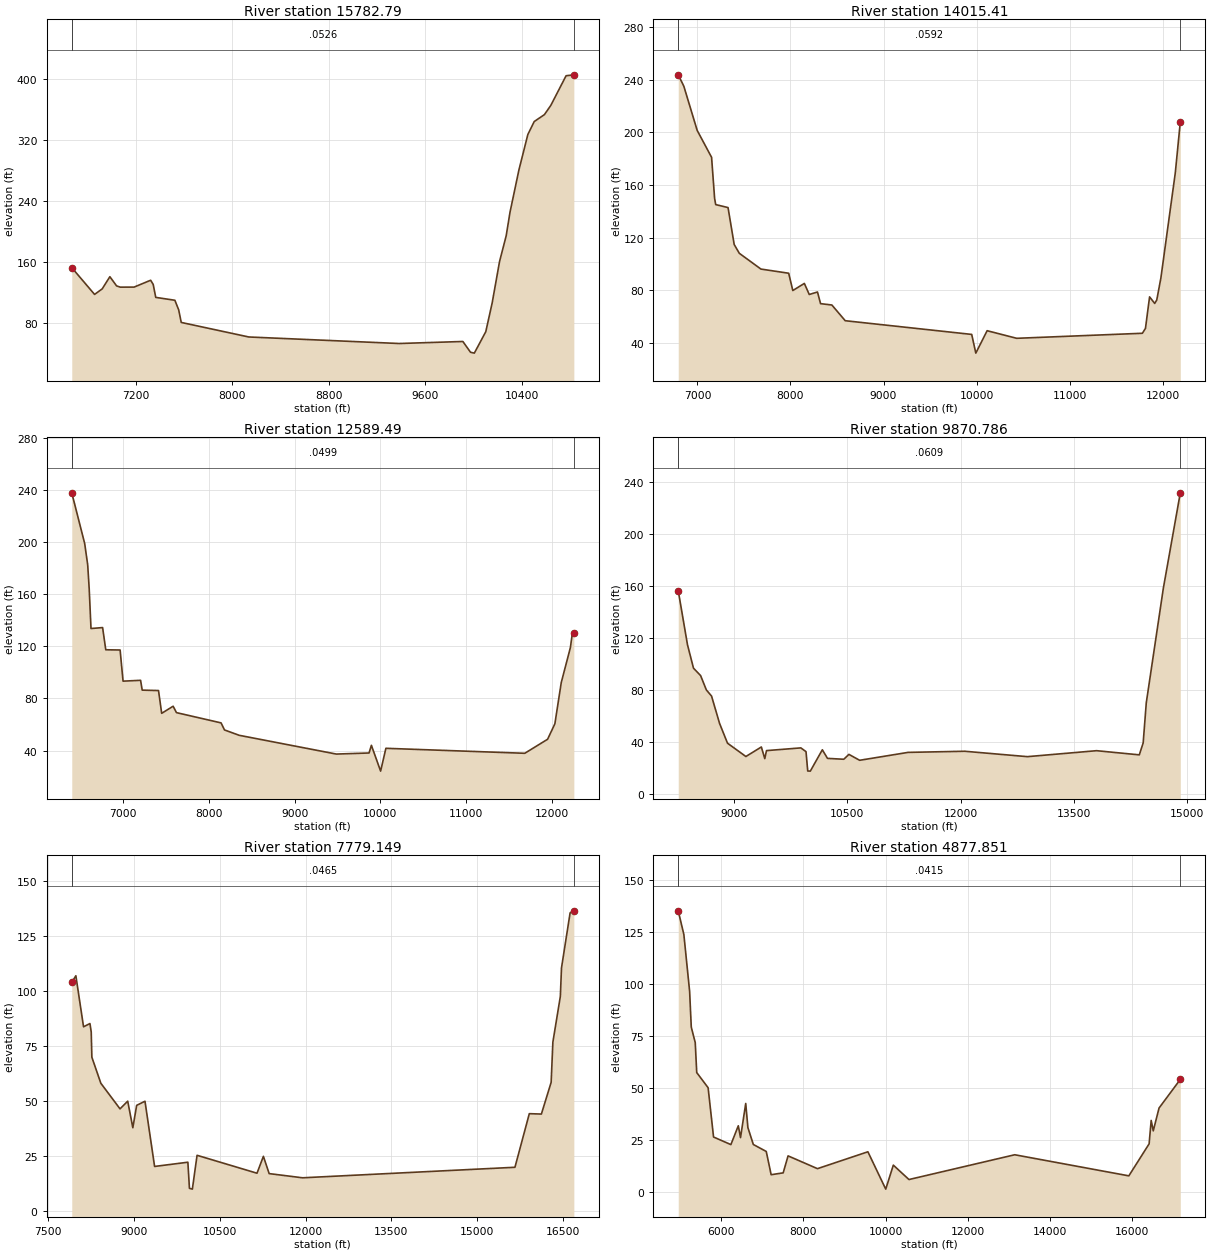
Type RM Length L Ch R = 1 ,15782.79,1767.379100,1767.379100,1767.379100
XS GIS Cut Line= 2
532464.020779997727925.541165411528524.106590182726575.241936028
#Sta/Elev= 30
 6669.31152.93836858.553 117.7696921.979125.10496985.405  141.057041.109 128.975
7071.953127.32877186.254127.40757323.677136.39057344.819130.90267365.961113.8957
7524.526110.12417556.23997.547257577.38181.017568137.64361.930179385.02153.35132
 9913.5756.021669976.99641.8859410008.7140.7349710103.8568.92021 10156.7106.6409
10218.05161.100910272.98194.7573 10304.7225.734710378.69281.259910452.69327.6897
10505.55344.691910590.11353.789710642.97365.849810769.82404.795810834.19406.0096
#Mann= 3 , 0 , 0
 6669.31  0.0526       0 6669.31  0.0526       010834.19  0.0526       0
#XS Ineff= 2 , 0
       08563.421                       0
Bank Sta=6669.31,10834.19
Exp/Cntr=0.3,0.1

Type RM Length L Ch R = 1 ,14015.41,1425.922000,1425.922000,1425.922000
XS GIS Cut Line= 2
533629.347512215727241.142925858528746.073586792724947.483960897
#Sta/Elev= 30
 6793.87243.66666853.914235.03096997.539 201.4337152.214180.97977184.669149.8406
7196.406145.05777328.984142.78767395.273 114.7147450.513108.02037682.52596.05461
7980.82492.886218025.01779.748998149.06585.145158201.78776.733528290.19678.63393
8323.31769.782538444.84768.737948588.47256.806669947.39446.392749991.58732.17647
10113.1249.2164510430.6943.4369211781.39 47.265511814.5350.9749511858.7274.92709
11913.9669.9432511936.0872.5791111980.25 89.267612134.93169.081512188.98207.8977
#Mann= 3 , 0 , 0
 6793.87  0.0592       0 6793.87  0.0592       012188.98  0.0592       0
#XS Ineff= 2 , 0
       09737.307                       0
Bank Sta=6793.87,12188.98
Exp/Cntr=0.3,0.1

Type RM Length L Ch R = 1 ,12589.49,2718.701100,2718.701100,2718.701100
XS GIS Cut Line= 4
533777.325509995726723.219933763532408.529030859725742.865698755
530854.760054618724411.063719079528857.057085097723689.670980111
#Sta/Elev= 30
6400.866237.6917 6551.33198.87546586.723182.41616603.896164.34486625.131  133.64
6760.434134.36536797.335117.3461 6964.55117.16936998.89793.287977203.24493.92864
7222.159 86.40377412.34886.076117449.24968.613017582.81274.062777621.45369.15395
8141.85361.278818181.36655.886538352.58651.769349485.27337.378669867.22538.20219
 9894.4244.1007210001.9824.2951510063.4441.7966811682.9837.9725711948.78 48.7213
12033.8460.6102312108.2692.2472512214.58118.999612235.84129.135512254.92129.9796
#Mann= 3 , 0 , 0
6400.866  0.0499       06400.866  0.0499       012254.92  0.0499       0
#XS Ineff= 2 , 0
       0                               0
Bank Sta=6400.866,12254.92
Exp/Cntr=0.3,0.1

Type RM Length L Ch R = 1 ,9870.786,2091.636700,2091.636700,2091.636700
XS GIS Cut Line= 4
534942.652242184724836.500462592 533000.44102183723782.157228678
531058.229801476 722801.80299367528857.057085097722265.382751852
#Sta/Elev= 30
8259.015156.68958381.507115.02348461.15696.937328555.60591.213518631.83380.13394
8700.10475.494138807.129 54.30228911.93139.119669155.243 28.88629360.05536.21958
9405.56927.247169428.32633.430299883.46435.520079951.73532.628939974.49217.72526
10008.6317.6190610167.9334.06511 10236.2 27.447510452.39 26.760910519.85 30.5215
10662.3725.9710111303.9732.0621312054.4932.9250312884.6228.7701513800.6733.35973
14366.7630.1547514418.2239.36409 14459.470.2753814685.83158.689814910.16232.0334
#Mann= 3 , 0 , 0
8259.015  0.0609       08259.015  0.0609       014910.16  0.0609       0
#XS Ineff= 2 , 0
       09894.799        13648.95       0
Bank Sta=8259.015,14910.16
Exp/Cntr=0.3,0.1

Type RM Length L Ch R = 1 ,7779.149,2901.298100,2901.298100,2901.298100
XS GIS Cut Line= 3
536218.962472677723430.709484071530965.743552923720785.602774456
528080.172596961720489.646778986
#Sta/Elev= 30
7908.902103.96297980.515106.95988114.869 83.7711 8226.8385.244418249.22381.43726
8260.41969.946118417.16558.136798753.04846.474278887.402 49.97678976.97137.89727
9044.14848.072729189.698 49.9461 9357.64  20.3149939.83822.23072 9967.28 10.3705
10018.2110.0062710100.6925.3789511149.0217.2380411260.9824.9009611361.7517.05751
11946.2515.1539115660.9819.9360615912.29 44.291616123.39 44.117516294.2858.53515
16324.4476.8161916455.1297.5836816475.23110.551516626.02135.558116691.18136.4647
#Mann= 3 , 0 , 0
7908.902  0.0465       07908.902  0.0465       016691.18  0.0465       0
#XS Ineff= 2 , 0
       09884.915         13859.6       0
Bank Sta=7908.902,16691.18
Exp/Cntr=0.3,0.1

Type RM Length L Ch R = 1 ,4877.851,2101.082300,2101.082300,2101.082300
XS GIS Cut Line= 5
538808.577433139723079.261739418537347.294705421 722098.90750441
535664.044981152721396.012015119531076.727051228 719453.80079481
527451.266106606719028.364051297
#Sta/Elev= 30
 4952.32134.9983 5089.09123.6551 5229.2196.357955269.71979.163345366.05571.71575
5402.18157.333575679.14650.055685811.60726.388176233.07622.741076413.86631.77785
6467.71426.095096594.33542.490196647.20830.917896779.49922.794227093.76819.45048
7212.973 8.286597505.5699.1711577624.77417.327378340.00711.189119566.707 19.2957
10001.081.36164210185.6912.8854110565.775.96582813139.4417.8643715915.717.735425
16409.07 23.105316459.4134.3455116509.7629.3471316650.7240.2978417167.9854.05115
#Mann= 3 , 0 , 0
 4952.32  0.0415       0 4952.32  0.0415       017167.98  0.0415       0
#XS Ineff= 2 , 0
       09574.066        12873.88       0
Bank Sta=4952.32,17167.98
Exp/Cntr=0.3,0.1

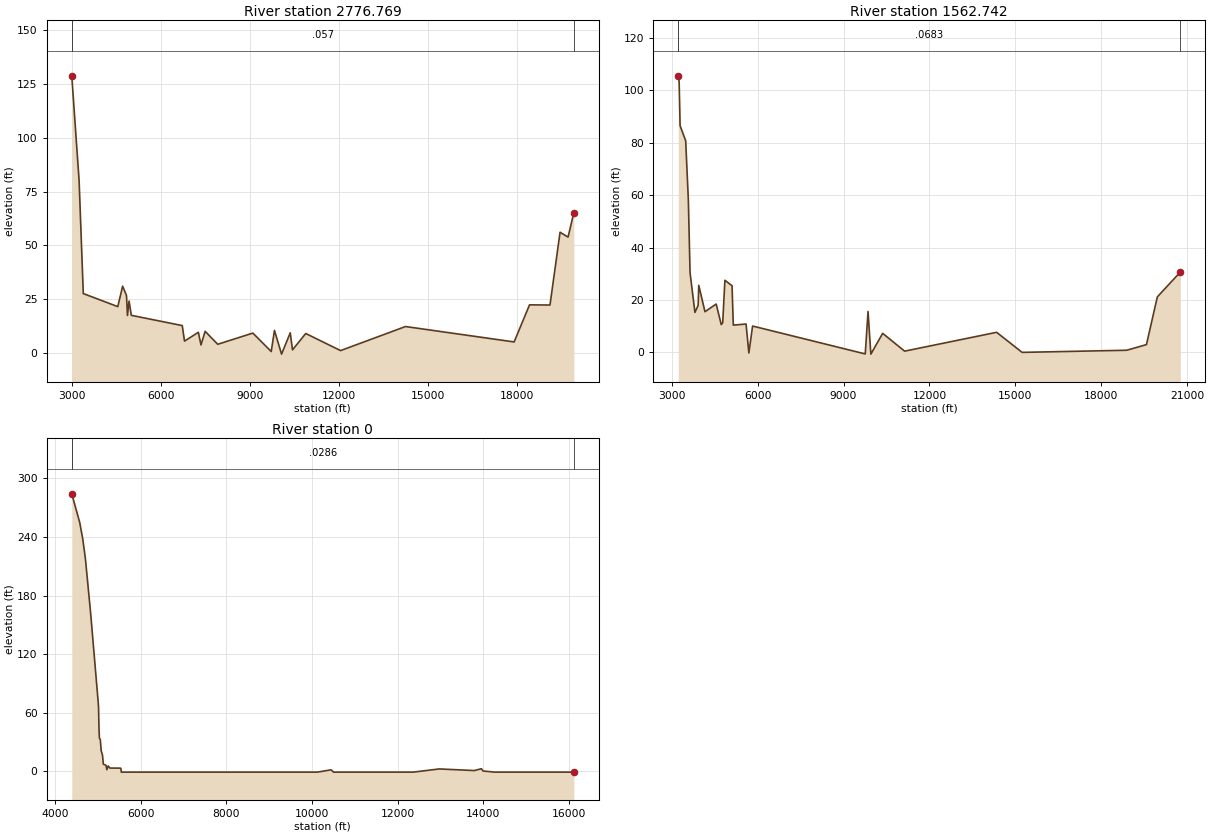
Type RM Length L Ch R = 1 ,2776.769,1214.026900,1214.026900,1214.026900
XS GIS Cut Line= 4
542452.535627484 722542.84149763534554.209998161719157.844799325
530965.743552953718085.004315689526359.928373247718029.512566552
#Sta/Elev= 30
2988.787128.88283236.33980.139893377.77427.52944  4541.921.455954705.09530.96334
4835.65126.65417 4868.2917.334124922.68824.050454998.84617.399526717.83512.63042
6793.9935.3964887261.8199.5206247349.6843.6228797490.2929.9602627914.5993.925447
9100.4849.1379799720.6250.5594729829.42210.3963310068.77-0.6561710362.539.259666
10438.681.33189410884.758.947323 12061.20.99018114253.05 12.184917918.255.016619
18438.2922.2804919128.3422.1965419468.3656.0730319738.3853.8205219933.4765.22832
#Mann= 3 , 0 , 0
2988.787   0.057       02988.787   0.057       019933.47   0.057       0
#XS Ineff= 2 , 0
       09840.796        13635.14       0
Bank Sta=2988.787,19933.47
Exp/Cntr=0.3,0.1

Type RM Length L Ch R = 1 ,1562.742,1562.741600,1562.741600,1562.741600
XS GIS Cut Line= 4
542674.502624094721303.525766551533684.839261353717474.595075026
531243.202298671716568.229838863 526082.46962747716586.727088585
#Sta/Elev= 30
 3226.43 105.5573258.497103.17963291.10586.528333486.752 80.78393579.936 58.0999
3638.92230.443183809.60915.260693921.523 17.94613943.26225.596684160.64815.53188
4551.94218.45658  4728.310.623644780.19711.321124856.28227.533475106.27525.43632
5149.75210.410425595.39310.842235693.216-0.213975823.64810.063149758.328-0.58366
9856.15115.610969953.975-0.6561710367.017.27208111133.61 0.4788714346.937.670595
 15237.40.01388918890.21 0.8242819580.212.98028919960.2221.1902620762.7530.65857
#Mann= 3 , 0 , 0
 3226.43  0.0683       0 3226.43  0.0683       020762.75  0.0683       0
#XS Ineff= 2 , 0
       09845.465        13573.24       0
Bank Sta=3226.43,20762.75
Exp/Cntr=0.3,0.1

Type RM Length L Ch R = 1 ,       0,0.000000,0.000000,0.000000
XS GIS Cut Line= 6
541815.674455532719450.281165327539062.276533591718852.258087259
538152.783102362718067.352797294537559.783357179717414.534902483
535094.018155718716270.299445522531711.366508212713960.982204738
#Sta/Elev= 30
4390.962 284.0794575.849254.93854647.481237.8791 4708.88217.89454831.678161.8676
5005.64272.098845015.87566.256635026.10844.135975036.34133.961295056.80732.84517
5077.27421.303395107.97316.880135128.4397.4341165189.8386.4207875210.3051.860793
5241.0045.6476515281.9373.4982165527.5323.4408275537.7653.1078335547.999-0.65617
10125.15-0.6561710442.631.69669410503.18-0.6561712362.36-0.6561712971.73 2.61154
13785.760.93961313953.372.80310613992.720.47379914267.21-0.6561716111.14-0.65617
#Mann= 3 , 0 , 0
4390.962  0.0286       04390.962  0.0286       016111.14  0.0286       0
#XS Ineff= 2 , 0
       0 9796.26        12882.45       0
Bank Sta=4390.962,16111.14
Exp/Cntr=0.3,0.1